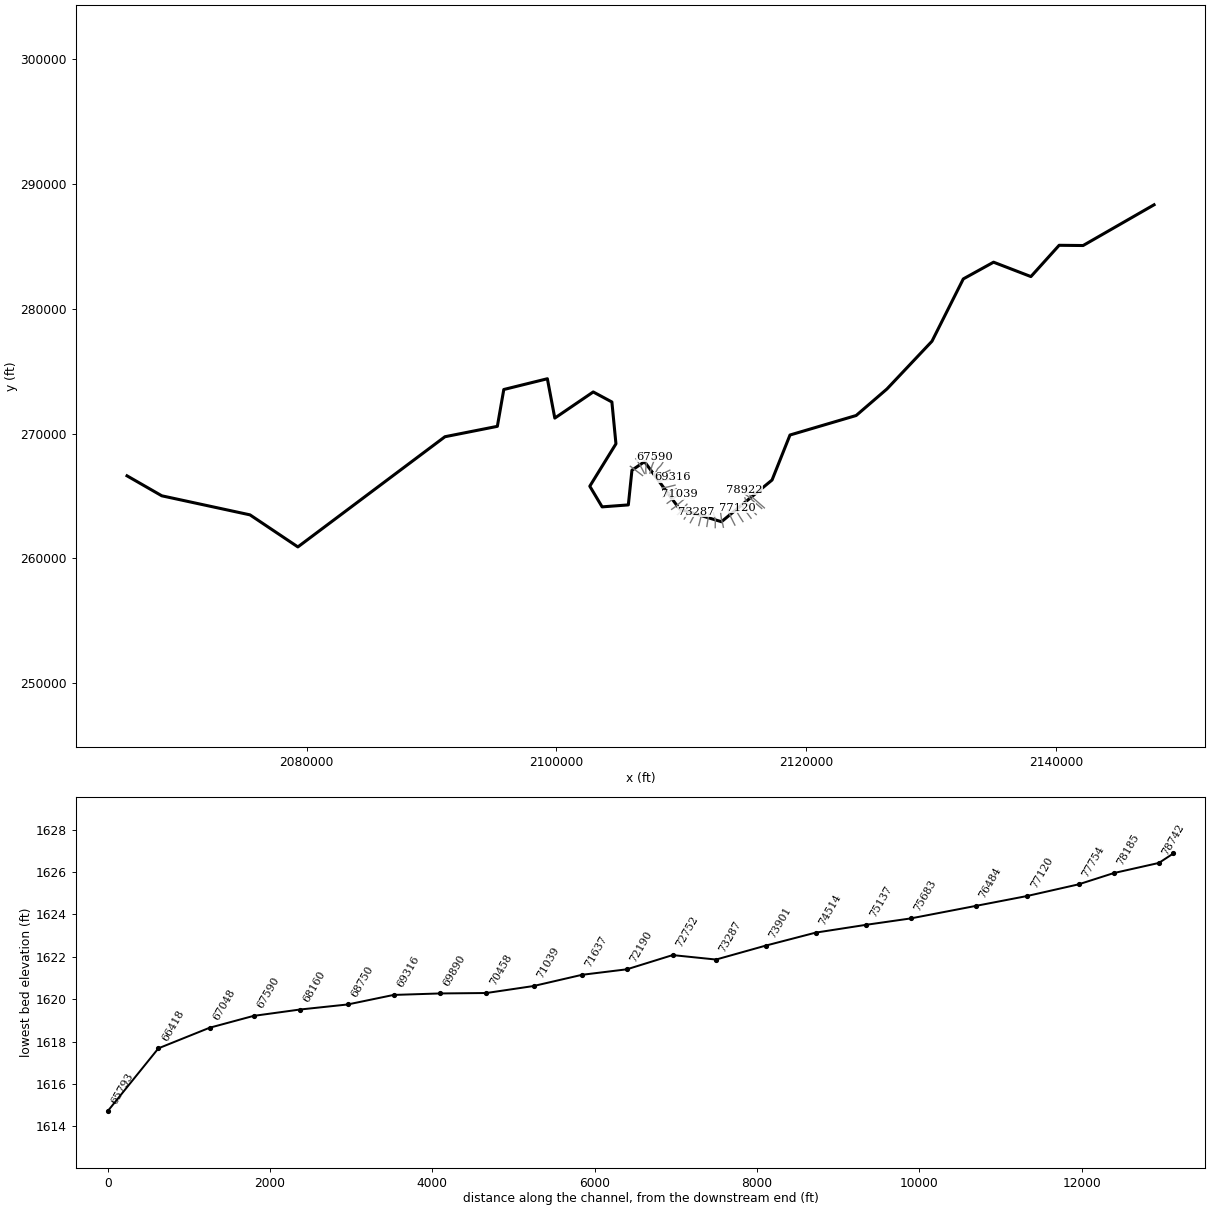
--- GRBRRV3.prj (project) ---

Proj Title=GRBRRV3
Current Plan=p01
Default Exp/Contr=0,0
English Units
Geom File=g01
Flow File=f01
Flow File=f02
Plan File=p01
Plan File=p02
BEGIN DESCRIPTION:
Stream Name- Greenbrier River 3
Greenbrier County, WV
WV Disaster Studies / PMR
WVDHSEM-2017-2, Flood Risk Project
HEC-RAS Version: 5.0.7
Upstream Extents: Approximately 10,000 feet downstream of Seneca Trail S
Downstream Extents:Approximately  21,000 feet downstream of Fort Spring Pike
General Notes:
For the Hydrology Regression with gage weighting was used.
END DESCRIPTION:
DSS File=dss
DSS Export Rating Curves= 0
DSS Export Rating Curve Sorted= 0
DSS Export Volume Flow Curves= 0
DXF Filename=GrbrRv2_AE.
DXF OffsetX= 0
DXF OffsetY= 0
DXF ScaleX= 0
DXF ScaleY= 0

--- GRBRRV3.p01 (plan) ---

Plan Title=Floodplain
Program Version=5.07
Short Identifier=Floodplain
Geom File=g01
Flow File=f01
Subcritical Flow
K Sum by GR= 0
Std Step Tol= 0.01
Critical Tol= 0.01
Num of Std Step Trials= 20
Max Error Tol= 0.3
Flow Tol Ratio= 0.001
Split Flow NTrial= 30
Split Flow Tol= 0.02
Split Flow Ratio= 0.02
Log Output Level= 0
Friction Slope Method= 1
Unsteady Friction Slope Method= 2
Unsteady Bridges Friction Slope Method= 1
Parabolic Critical Depth
Global Vel Dist= 0 , 0 , 0
Global Log Level= 0
CheckData=True
Encroach Param=-1 ,0,0, 0
Computation Interval=0.1SEC
Output Interval=1MIN
Instantaneous Interval=Max Profile
Mapping Interval=1HOUR
Computation Time Step Use Courant=        0
Computation Time Step Use Time Series=    0
Computation Time Step Count To Double=0
Computation Time Step Max Doubling=0
Computation Time Step Max Halving=0
Computation Time Step Residence Courant=0
Run HTab= 0
Run UNet= 0
Run Sediment= 0
Run PostProcess= 0
Run WQNet= 0
Run RASMapper= 0
UNET Theta= 0
UNET Theta Warmup= 0
UNET ZTol= 0
UNET ZSATol= 0
UNET MxIter= 0
UNET Max Iter WO Improvement= 0
UNET MaxInSteps= 0
UNET DtIC= 0
UNET DtMin= 0
UNET MaxCRTS= 0
UNET WFStab= 0
UNET SFStab= 0
UNET WFX= 1
UNET SFX= 1
UNET 1D Methodology=Finite Difference
UNET DSS MLevel= 1
UNET Pardiso=0
UNET DZMax Abort= 0
UNET Use Existing IB Tables= 0
UNET Froude Reduction=False
UNET Froude Limit= 0
UNET Froude Power= 0
UNET D1 Cores= 0
UNET D2 Coriolis=0
UNET D2 Cores= 0
UNET D2 Theta= 1
UNET D2 Theta Warmup= 1
UNET D2 Z Tol= 0.01
UNET D2 Volume Tol= 0.01
UNET D2 Max Iterations= 20
UNET D2 Equation= 0
UNET D2 RampUpFraction=0.1
UNET D2 TimeSlices= 1
UNET D2 BCVolumeCheck=0
UNET D1D2 MaxIter= 0
UNET D1D2 ZTol=0.01
UNET D1D2 QTol=0.1
UNET D1D2 MinQTol=1
DSS File=dss
Write IC File= 0
Write IC File at Fixed DateTime=0
Write IC File at Sim End=0
Echo Input=False
Echo Parameters=False
Echo Output=False
Write Detailed= 0
HDF Write Warmup=0
HDF Write Time Slices=0
HDF Flush=0
HDF Face Node Velocities=0
HDF Compression= 1
HDF Chunk Size= 1
HDF Spatial Parts= 1
HDF Use Max Rows=0
HDF Fixed Rows= 1
Calibration Method= 0
Calibration Iterations= 20
Calibration Max Change=0.05
Calibration Tolerance=0.2
Calibration Maximum=1.5
Calibration Minimum=0.5
Calibration Optimization Method= 1
WQ AD Non Conservative
WQ ULTIMATE=-1
WQ Max Comp Step=1HOUR
WQ Output Interval=15MIN
WQ Output Selected Increments= 0
WQ Output face flow=0
WQ Output face velocity=0
WQ Output face area=0
WQ Output face dispersion=0
WQ Output cell volume=0
WQ Output cell surface area=0
WQ Output cell continuity=0
WQ Output cumulative cell continuity=0
WQ Output face conc=0
WQ Output face dconc_dx=0
WQ Output face courant=0
WQ Output face peclet=0
WQ Output face adv mass=0
WQ Output face disp mass=0
WQ Output cell mass=0
WQ Output cell source sink temp=0
WQ Output nsm pathways=0
WQ Output nsm derived pathways=0
WQ Output MaxMinRange=-1
WQ Daily Max Min Mean=-1
WQ Daily Range=0
WQ Daily Time=0
WQ Create Restart=0
WQ Fixed Restart=0
WQ System Summary=0
WQ Write To DSS=0
WQ Use Fixed Temperature=0
Sorting and Armoring Iterations= 10
XS Update Threshold= 0.02
Bed Roughness Predictor= 0
Hydraulics Update Threshold= 0.02
Energy Slope Method= 1
Volume Change Method= 1
Sediment Retention Method= 0
XS Weighting Method= 0
Number of US Weighted Cross Sections= 1
Number of DS Weighted Cross Sections= 1
Upstream XS Weight=0
Main XS Weight=1
Downstream XS Weight=0
Number of DS XS's Weighted with US Boundary= 1
Upstream Boundary Weight= 1
Weight of XSs Associated with US Boundary= 0
Number of US XS's Weighted with DS Boundary= 1
Downstream Boundary Weight= 0.5
Weight of XSs Associated with DS Boundary= 0.5
Percentile Method= 0
Sediment Output Level= 3
Mass or Volume Output= 0
Output Increment Type= 1
Profile and TS Output Increment= 1
XS Output Flag= 0
XS Output Increment= 10
Write Gradation File= 0
Read Gradation Hotstart= 0
Write HDF5 File= 1
Write Binary Output= 1
Write DSS Sediment File= 0
SV Curve= 0
Specific Gage Flag= 0

--- GRBRRV3.p02 (plan) ---

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Plan Title=Floodway
Short Identifier=Floodway
Geom File=g01
Flow File=f02
Encroach Param=-1 ,0,0, 2
Encroach River=GRBRRV3
Encroach Reach=Main
Encroach Node=78922
       1   785.1    1145
Encroach Node=78742
       1   648.4    1000
Encroach Node=78185
       1   652.6    1018
Encroach Node=77754
       1     618     990
Encroach Node=77120
       1     427   831.3
Encroach Node=76484
       1   416.3     770
Encroach Node=75683
       1     305     590
Encroach Node=75137
       1     265     560
Encroach Node=74514
       1     215  531.73
Encroach Node=73901
       1     267     608
Encroach Node=73287
       1     295     590
Encroach Node=72752
       1     295     600
Encroach Node=72190
       1     327     650
Encroach Node=71637
       1     398     725
Encroach Node=71039
       1     290     675
Encroach Node=70458
       1     313     680
Encroach Node=69890
       1   183.5     535
Encroach Node=69316
       1     340     630
Encroach Node=68750
       1     190  523.84
Encroach Node=68160
       1     152  677.63
Encroach Node=67590
       1  246.83  902.73
Encroach Node=67048
       1  327.48 1039.78
Encroach Node=66418
       1     450   999.9
Encroach Node=65793
       1     570  1013.2
Encroach Node=65289
       1  536.28   975.6
Encroach Node=64758
       1  467.15  902.77
Encroach Node=64153
       1   489.3   899.4
Encroach Node=63357
       1 1004.75 1419.75
Encroach Node=62946
       1     540    1050
Encroach Node=62361
       1     247   605.6
Encroach Node=61267
       1   201.7     650
Encroach Node=60363
       1   278.6  804.53
Encroach Node=59151
       1   366.5  892.78
Encroach Node=57982
       1     394  856.38
Encroach Node=57400
       1     416  872.93
Encroach Node=56327
       1     399     850
Encroach Node=55823
       1  316.42     772
Encroach Node=55432
       1  542.38  998.15
Encroach Node=55024
       1     650    1150
Encroach Node=54791
       1     759    1220
Encroach Node=54579
       1     900    1247
Encroach Node=54245
       1   317.3 1160.52
Encroach Node=53439
       1   317.3  1203.8
Encroach Node=52828
       1   362.9 1127.95
Encroach Node=52277
       1     500     980
Encroach Node=51735
       1  412.37     800
Encroach Node=51173
       1  270.89  726.22
Encroach Node=50748
       1   155.8   648.7
Encroach Node=49907
       1     650  1122.7
Encroach Node=49348
       1     690 1169.06
Encroach Node=48655
       1  696.18 1148.53
Encroach Node=48055
       1     800 1155.44
Encroach Node=47480
       1     765  1083.2
Encroach Node=47039
       1     685  1005.6
Encroach Node=46605
       1     775 1115.23
Encroach Node=45997
       1    1000    1350
Encroach Node=45495
       1  189.45     500
Encroach Node=45352
       1     115     545
Encroach Node=45254
       1     119     550
Encroach Node=45124
       1  129.26     580
Encroach Node=44939
       1  151.88     590
Encroach Node=44704
       1  137.82     415
Encroach Node=44215
       1  239.28     490
Encroach Node=43816
       1   182.5  502.66
Encroach Node=43230
       1  282.44     630
Encroach Node=42658
       1  396.89     750
Encroach Node=42104
       1     610 1022.96
Encroach Node=41788
       1   693.1    1000
Encroach Node=41114
       1     702 1092.73
Encroach Node=40678
       1     550  1014.2
Encroach Node=40094
       1  281.96     680
Encroach Node=39315
       1  152.49     475
Encroach Node=38955
       1  207.82     580
Encroach Node=38368
       1  204.83   564.6
Encroach Node=37763
       1   237.8  530.16
Encroach Node=37542
       1  528.06  789.79
Encroach Node=37178
       1   897.5  1176.6
Encroach Node=36567
       1  677.51 1027.19
Encroach Node=36304
       1  813.54  1087.6
Encroach Node=36009
       1  665.38   949.4
Encroach Node=35372
       1  326.87     713
Encroach Node=34668
       1  162.79  508.62
Encroach Node=34061
       1   253.8  605.75
Encroach Node=33488
       1  290.45  610.25
Encroach Node=32897
       1  882.82 1182.89
Encroach Node=32409
       1    1451    1806
Encroach Node=32125
       1     554     916
Encroach Node=31580
       1     290     600
Encroach Node=31013
       1   325.5   560.7
Encroach Node=30141
       1   301.4  587.71
Encroach Node=29560
       1  274.86  576.48
Encroach Node=28958
       1  308.85  580.89
Encroach Node=28385
       1     221   451.8
Encroach Node=27784
       1   207.2  434.34
Encroach Node=27168
       1     190   500.5
Encroach Node=26723
       1  245.28  590.69
Encroach Node=26311
       1   226.6  768.79
Encroach Node=25695
       1     220     920
Encroach Node=25141
       1     420     770
Encroach Node=24662
       1     400     645
Encroach Node=23865
       1     635     855
Computation Interval=1MIN
Output Interval=1HOUR

--- GRBRRV3.f01 (steady flow) ---

Flow Title=NFF Regression Equation
Program Version=5.07
Number of Profiles= 6
Profile Names=f1p,f10p,f4p,f2p,f02p,f1pplus
River Rch & RM=GRBRRV3,Main            ,78922
   71602   48316   57736   64747   87932   79052
River Rch & RM=GRBRRV3,Main            ,78742
   72324   48818   58327   65400   88792   79849
River Rch & RM=GRBRRV3,Main            ,63357
   81838   55434   66115   74002  100119   90352
River Rch & RM=GRBRRV3,Main            ,23865
   81990   55540   66240   74140  100300   90520
Boundary for River Rch & Prof#=GRBRRV3,Main            , 1
Up Type= 0
Dn Type= 1
Dn Known WS=1580.17
Boundary for River Rch & Prof#=GRBRRV3,Main            , 2
Up Type= 0
Dn Type= 1
Dn Known WS=1575.47
Boundary for River Rch & Prof#=GRBRRV3,Main            , 3
Up Type= 0
Dn Type= 1
Dn Known WS=1577.48
Boundary for River Rch & Prof#=GRBRRV3,Main            , 4
Up Type= 0
Dn Type= 1
Dn Known WS=1578.85
Boundary for River Rch & Prof#=GRBRRV3,Main            , 5
Up Type= 0
Dn Type= 1
Dn Known WS=1582.95
Boundary for River Rch & Prof#=GRBRRV3,Main            , 6
Up Type= 0
Dn Type= 1
Dn Known WS=1581.53
Gate Openings=GRBRRV3,Main,117567  ,Gate #1                         ,
       2       2       0       0       0       0       0       0       0       0
       0       0
DSS Import GetInterval= 0
DSS Import GetPeak= 0
DSS Import FillOption= 0

--- GRBRRV3.f02 (steady flow) ---

Flow Title=Floodway
Program Version=5.07
Number of Profiles= 2
Profile Names=f1p,Floodway
River Rch & RM=GRBRRV3,Main            ,78922
   71602   71602
River Rch & RM=GRBRRV3,Main            ,78742
   72324   72324
River Rch & RM=GRBRRV3,Main            ,63357
   81838   81838
River Rch & RM=GRBRRV3,Main            ,23865
   81990   81990
Boundary for River Rch & Prof#=GRBRRV3,Main            , 1
Up Type= 0
Dn Type= 1
Dn Known WS=1580.17
Boundary for River Rch & Prof#=GRBRRV3,Main            , 2
Up Type= 0
Dn Type= 1
Dn Known WS=1580.91
Gate Openings=GrbrRv2_AE      ,Main            ,117567  ,Gate #1                         ,
       2       2       0       0
DSS Import GetInterval= 0
DSS Import GetPeak= 0
DSS Import FillOption= 0

--- GRBRRV3.g01 (geometry) ---

Geom Title=USGS 10m DEM
Program Version=5.07

River Reach=GRBRRV3         ,Main
Reach XY= 30
     2147853.903288318.4270000012142171.14800003285056.311000019
2140252.74700004285074.9310000092137992.79400003 282569.21100001
2135001.75099999283721.8900000012132578.70100001282382.555000022
2130070.27500004277390.5530000032126465.11000004273568.732999995
2123999.83200002271443.7329999952118701.22099999269881.232999995
2117263.72099999266277.0660000152113214.12500003262937.376000017
2109857.02700001263954.0929999952107051.02300003267747.055000007
2106045.64300001 267060.005000012105756.61700001264284.151999995
2103657.17400002264126.9470000122102670.62800002265781.803000018
     2104764.748269176.3920000052104439.43399999272526.311000019
2102946.13100001273330.069000021     2099868.465271235.292999998
2099273.02200001274387.6159999972095783.85699999273525.399000019
2095268.35600001270575.9080000222091072.92199999269744.296000019
2079295.30000004260919.2100000082075461.96599999263486.918000013
2068399.46599999265012.959999993 2065614.1903584266612.791144013

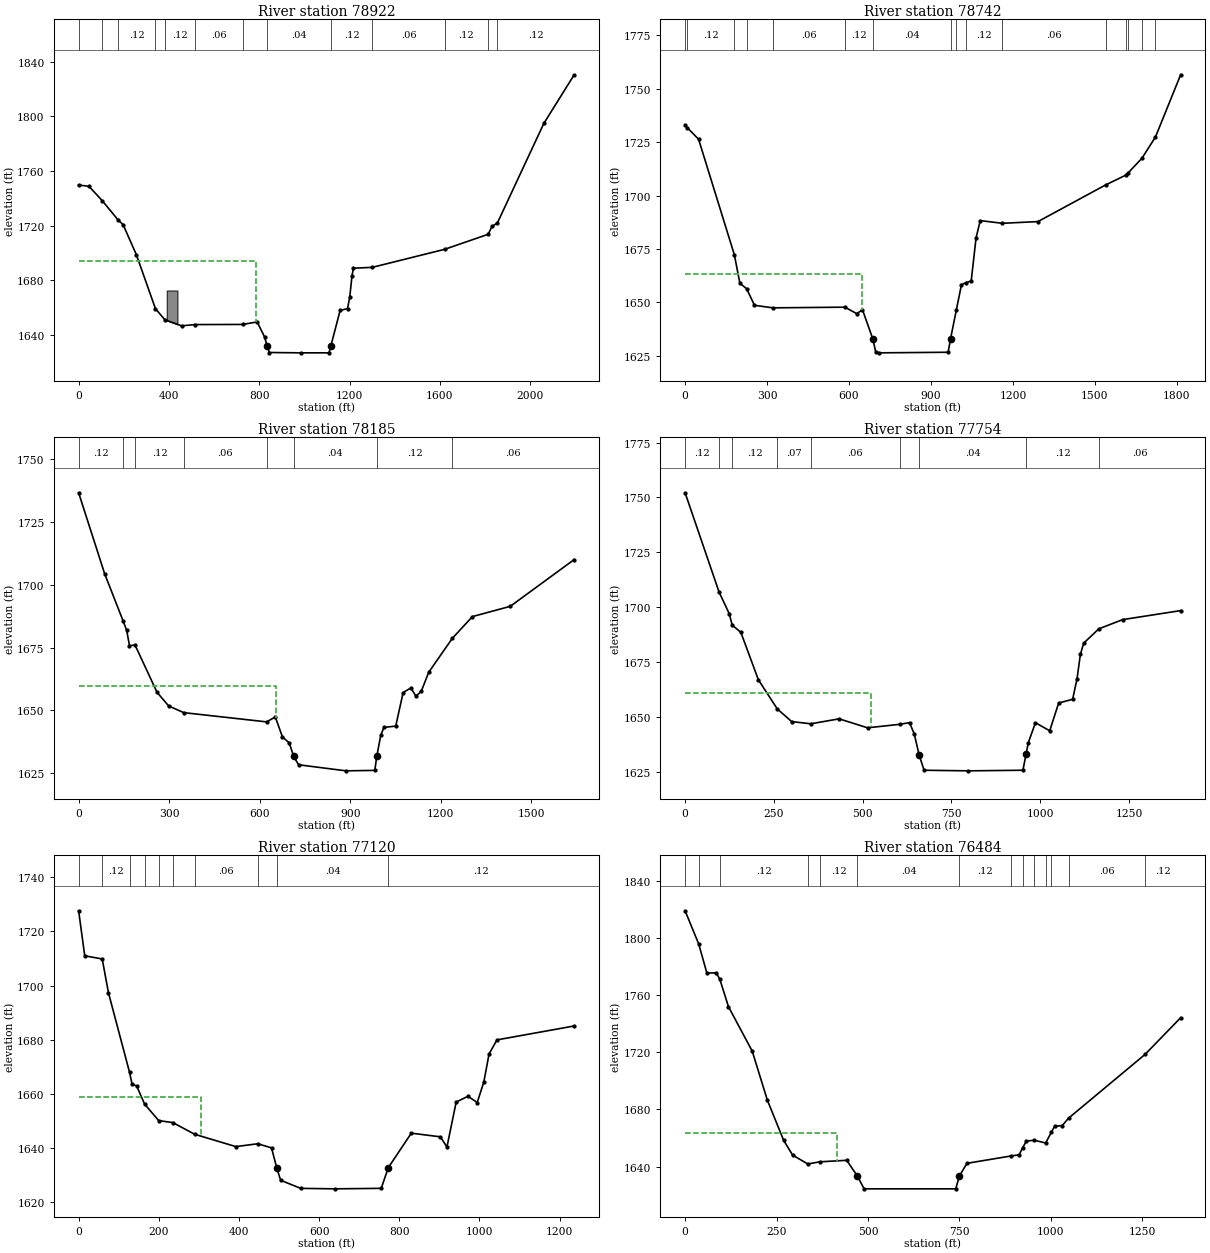
Type RM Length L Ch R = 1 ,78922   ,177.8,179.6,174.4
XS GIS Cut Line= 2
     2116651.272      264044.102     2115005.438      265495.491
#Sta/Elev= 30
       0 1749.64    45.9 1748.68   104.8 1738.14   176.5 1723.73   196.8 1720.71
   255.8 1698.61   340.2 1659.18   381.9 1651.07   455.9 1646.62   514.9 1647.55
   726.6 1647.65   790.5  1649.5   823.3 1638.57   834.4 1632.05   844.6 1627.12
   984.6 1626.88  1108.7 1626.88  1117.1 1632.02  1157.9 1657.87  1190.7 1659.26
  1200.5 1667.54  1210.4 1683.05  1216.9  1688.8  1300.4 1689.42  1620.4 1702.59
  1813.6  1713.6  1830.3 1719.34    1854 1721.75  2059.9 1794.65  2194.4 1830.29
#Mann= 13 ,-1 , 0
       0     .12       0   104.8     .06       0   176.5     .12       0
   340.2    .016       0   381.9     .12       0   514.9     .06       0
   726.6     .12       0   834.4     .04       0  1117.1     .12       0
  1300.4     .06       0  1620.4     .12       0  1813.6    .016       0
    1854     .12       0
#XS Ineff= 2 , 0
           785.1 1694.38
Permanent Ineff=
       F       F
#Block Obstruct= 1 ,-1
     390   437.5 1672.47
Bank Sta=834.4,1117.1
XS Rating Curve= 0 ,0
Exp/Cntr(USF)=0,0
Exp/Cntr=0.3,0.1

Type RM Length L Ch R = 1 ,78742   ,606,557.1,547.7
XS GIS Cut Line= 5
     2116438.382      263999.589     2116010.144      264372.748
     2115661.675      264685.611       2115332.6       264974.19
     2115060.136      265177.502
#Sta/Elev= 30
       0 1732.82    8.121731.713    49.4 1726.31  180.461672.224   200.5 1658.99
  225.421656.372     254 1648.66  321.561647.468   584.81647.787   628.4 1644.76
   649.3 1646.58   687.1 1632.96   698.1  1626.7  710.43 1626.43   962.9  1626.7
   971.9 1633.12  993.161646.611  1011.7  1658.3  1026.91659.186  1047.3 1660.03
  1065.2 1680.25  1080.5 1688.27 1161.161687.007  1291.7 1687.81 1539.331704.948
 1613.04 1709.51 1622.971710.739 1672.351717.433 1721.741727.346    1814 1756.46
#Mann= 16 ,-1 , 0
       0     .06       0    8.12     .12       0  180.46    .016       0
  225.42     .12       0  321.56     .06       0   584.8     .12       0
   687.1     .04       0   971.9     .12       0  993.16     .08       0
  1026.9     .12       0 1161.16     .06       0 1539.33     .12       0
 1613.04     .06       0 1622.97     .12       0 1672.35    .016       0
 1721.74     .12       0
#XS Ineff= 2 , 0
          648.37 1663.28
Permanent Ineff=
       F       F
Bank Sta=687.1,971.9
XS Rating Curve= 0 ,0
Exp/Cntr=0.3,0.1

Type RM Length L Ch R = 1 ,78185   ,451.7,431.3,422.5
XS GIS Cut Line= 4
2115997.50727169263508.469273595     2115600.084      263936.263
     2115302.398      264305.804     2115085.905      264847.326
#Sta/Elev= 30
       0 1736.57    86.2 1704.36  146.751685.757   159.2 1681.85   168.4 1675.79
  187.071675.943   259.7 1657.19   298.4 1651.75  348.321649.103  622.811645.426
   651.6 1647.39     675 1639.48   697.7 1637.05   712.3 1631.74   728.6 1628.36
  885.84 1625.95   981.1 1626.13  987.87 1631.83    1001 1640.16  1011.4 1643.22
  1050.5 1643.75  1074.9 1657.08  1100.5 1658.93  1117.3 1655.66  1134.9 1657.54
  1159.7 1665.16 1237.991678.663  1304.5 1687.32  1429.8 1691.39  1641.6    1710
#Mann= 8 ,-1 , 0
       0     .12       0  146.75    .016       0  187.07     .12       0
  348.32     .06       0  622.81     .12       0   712.3     .04       0
  987.87     .12       0 1237.99     .06       0
#XS Ineff= 2 , 0
          652.49 1659.65
Permanent Ineff=
       F       F
Bank Sta=712.3,987.87
XS Rating Curve= 0 ,0
Exp/Cntr=0.3,0.1

Type RM Length L Ch R = 1 ,77754   ,654.1,633.4,612.8
XS GIS Cut Line= 4
2115583.68913537263214.487660153      2115225.02      263692.848
     2115026.545      263971.755     2114762.728      264342.465
#Sta/Elev= 30
       0 1752.14    95.71706.877   124.3 1697.02  132.611691.845     157 1688.53
   206.2 1666.97  259.491653.642     300 1647.87  354.111646.854   433.6 1649.12
   513.7 1645.03   604.41646.617     632 1647.39   645.6 1642.03   658.8 1632.67
   672.9 1625.69  797.66 1625.42   951.1 1625.69     960 1633.01   966.2 1638.19
   986.4 1647.36  1026.6 1643.67  1051.7 1656.31  1091.1 1658.03  1103.5 1667.38
  1112.9 1678.48  1122.3 1683.63 1164.821690.137    1232 1694.34  1395.2 1698.44
#Mann= 9 ,-1 , 0
       0     .12       0    95.7    .016       0  132.61     .12       0
  259.49     .07       0  354.11     .06       0   604.4     .12       0
   658.8     .04       0     960     .12       0 1164.82     .06       0
#XS Ineff= 2 , 0
          524.78 1660.85
Permanent Ineff=
       F       F
Bank Sta=658.8,960
XS Rating Curve= 0 ,0
Exp/Cntr=0.3,0.1

Type RM Length L Ch R = 1 ,77120   ,666.3,636.1,627.5
XS GIS Cut Line= 4
     2114936.212      262946.343     2114686.229      263329.912
     2114492.798      263650.056     2114498.376       264054.44
#Sta/Elev= 30
       0 1727.62    15.2 1710.99   58.851709.809    74.4 1697.33  127.061667.895
   133.2 1663.61   144.9 1662.85  164.611656.168  199.87 1650.08  235.131649.351
  289.371645.036   392.2 1640.48  446.661641.524   481.2 1640.02   494.4 1632.55
     504 1628.03     554 1625.05  639.15 1624.87   754.9 1625.05   772.5 1632.67
     830 1645.44   902.5 1644.09   918.9 1640.34   941.9 1656.93   971.4 1659.09
   994.4 1656.77  1010.8 1664.28  1023.9 1674.68  1043.6 1679.91  1236.3 1685.05
#Mann= 10 ,-1 , 0
       0    .016       0   58.85     .12       0  127.06    .016       0
  164.61     .12       0  199.87    .016       0  235.13     .12       0
  289.37     .06       0  446.66     .12       0   494.4     .04       0
   772.5     .12       0
#XS Ineff= 2 , 0
          305.77  1658.9
Permanent Ineff=
       F       F
Bank Sta=494.4,772.5
XS Rating Curve= 0 ,0
Exp/Cntr=0.3,0.1

Type RM Length L Ch R = 1 ,76484   ,838.7,800.8,746.3
XS GIS Cut Line= 4
2114289.53749952262666.929251193     2114108.629      263023.675
     2113928.286       263392.382113740.32783459 263903.04457601
#Sta/Elev= 30
       0 1819.22   37.341795.874    59.5 1775.61    85.3 1775.71   95.011771.188
   118.5 1752.06   183.5 1720.87     225 1686.44   269.2 1658.48     294 1648.02
   335.41641.817  368.521643.346   441.8 1644.39     471 1633.33   489.3  1624.4
   739.9  1624.4   749.7 1633.36   770.5 1642.27  891.221647.443   913.3 1648.27
  922.69 1653.22     933 1657.81  954.17 1658.47  985.641656.516  1000.81663.894
  1009.9 1668.18  1030.9 1668.73 1048.591673.994 1257.371718.599  1354.6 1744.27
#Mann= 14 ,-1 , 0
       0     .12       0   37.34    .016       0   95.01     .12       0
   335.4    .016       0  368.52     .12       0     471     .04       0
   749.7     .12       0  891.22    .016       0  922.69     .12       0
  954.17     .08       0  985.64     .06       0  1000.8    .016       0
 1048.59     .06       0 1257.37     .12       0
#XS Ineff= 2 , 0
          416.24  1663.2
Permanent Ineff=
       F       F
Bank Sta=471,749.7
XS Rating Curve= 0 ,0
Exp/Cntr=0.3,0.1

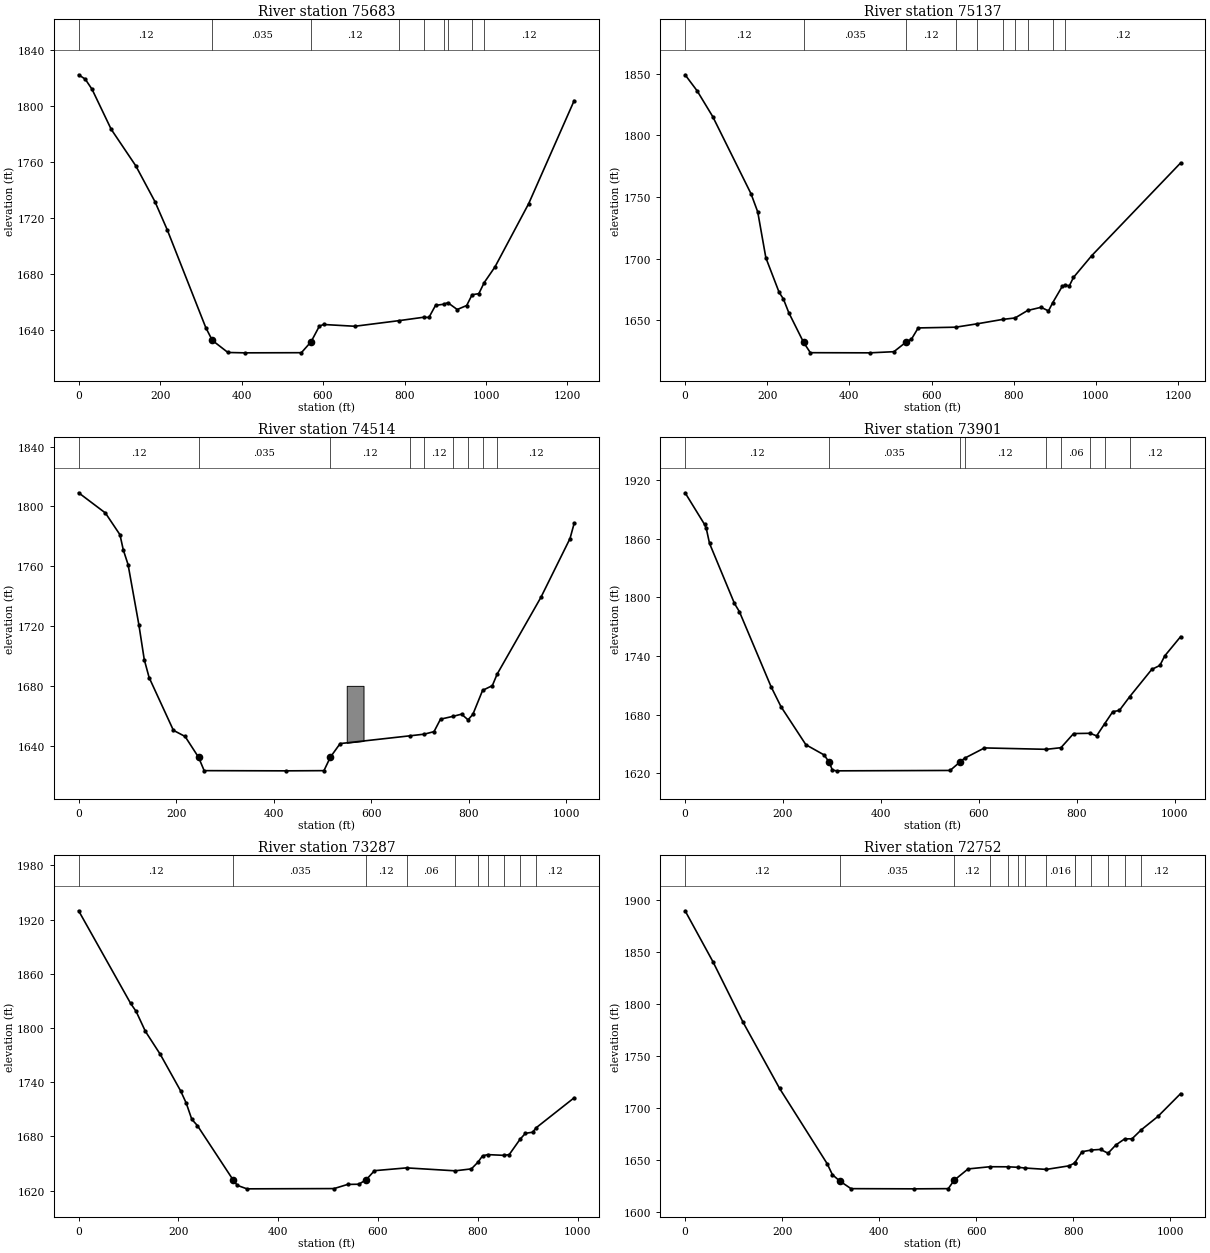
Type RM Length L Ch R = 1 ,75683   ,585.8,546.7,507
XS GIS Cut Line= 4
     2113368.775      262494.169     2113314.577       262749.29
     2113218.195      263101.6952113141.85918208263687.040020494
#Sta/Elev= 30
       0 1822.59    16.2 1819.48      33 1812.19    79.9 1783.64   140.3 1757.51
   187.3 1731.94   217.5 1711.79   312.1 1641.88   328.1 1632.74   366.5 1624.06
  407.32 1623.81   546.8 1623.91   570.6 1631.72     591  1642.9   601.2 1644.08
     678 1642.81  787.211646.852  846.78 1649.25   859.9 1649.09   876.1  1657.7
  896.88 1658.61  906.361659.667   929.4 1654.78   952.6 1657.64  965.931665.338
   982.4 1666.12  995.72 1674.06  1022.1 1685.24  1104.8 1730.46  1216.5 1804.12
#Mann= 9 ,-1 , 0
       0     .12       0   328.1    .035       0   570.6     .12       0
  787.21    .016       0  846.78     .12       0  896.88     .08       0
  906.36     .12       0  965.93    .016       0  995.72     .12       0
Bank Sta=328.1,570.6
XS Rating Curve= 0 ,0
Exp/Cntr=0.3,0.1

Type RM Length L Ch R = 1 ,75137   ,641.5,622.8,563.8
XS GIS Cut Line= 4
     2112714.829      262464.367      2112715.92      262641.199
     2112722.509      263075.8762112572.08484223263651.308838415
#Sta/Elev= 30
       0 1849.24    29.3  1836.2    67.2 1815.34   160.5 1752.63   176.8 1737.93
   196.6 1700.67     229 1672.52   239.2 1667.32   252.4 1656.13   288.5 1631.97
   304.9 1623.63  450.11 1623.51   508.3 1624.44   537.8 1632.21     551  1634.6
   567.4 1643.73  658.641644.329  711.691647.114  772.741650.631  803.271651.825
   833.8  1657.9   866.6 1660.48   884.6 1657.54  894.861664.207   918.5 1677.71
  925.391678.409   935.5    1678   945.4 1684.72   989.8 1702.39  1206.3  1777.7
#Mann= 10 ,-1 , 0
       0     .12       0   288.5    .035       0   537.8     .12       0
  658.64    .016       0  711.69     .12       0  772.74    .016       0
  803.27     .12       0   833.8     .08       0  894.86    .016       0
  925.39     .12       0
Bank Sta=288.5,537.8
XS Rating Curve= 0 ,0
Exp/Cntr=0.3,0.1

Type RM Length L Ch R = 1 ,74514   ,623,612.5,592.5
XS GIS Cut Line= 3
     2112042.966      262560.727     2112113.038      263010.299
2112199.84647712263565.077999046
#Sta/Elev= 30
       0 1809.16    54.9 1795.65    84.8 1781.09    91.5 1771.08   101.4 1761.14
   123.6 1720.83   134.6 1697.59   144.6 1685.54   194.4 1650.25   218.4 1646.13
  246.02 1632.19   257.5 1623.27  425.19 1623.14   503.2 1623.27   516.5 1632.36
   536.4 1641.37  679.191646.559  709.091647.685     729 1649.37   742.3  1657.7
  768.881659.669   785.5 1661.06  798.781657.268   808.7 1660.92  828.671676.981
   848.6 1680.14  858.57 1687.89   948.2 1739.16    1008 1778.57  1016.5 1788.75
#Mann= 9 ,-1 , 0
       0     .12       0  246.02    .035       0   516.5     .12       0
  679.19    .016       0  709.09     .12       0  768.88     .08       0
  798.78     .12       0  828.67    .016       0  858.57     .12       0
#Block Obstruct= 1 ,-1
  549.97  584.36    1680
Bank Sta=246.02,516.5
XS Rating Curve= 0 ,0
Exp/Cntr=0.3,0.1

Type RM Length L Ch R = 1 ,73901   ,646.8,614.3,549.8
XS GIS Cut Line= 4
     2111396.079      262632.341     2111461.992      262882.361
     2111551.864      263252.329 2111602.2223408263621.612976644
#Sta/Elev= 30
       0 1907.08    39.8 1874.64    43.2  1870.7    49.9 1855.29   100.8 1793.84
     111 1785.32   175.5 1708.72   195.8 1688.22   246.7 1649.24   283.9  1638.8
     294 1631.55   300.8 1623.34  309.21 1622.53   541.2 1622.92   560.8 1631.33
   570.6 1635.39   611.4 1645.98  737.771644.549  767.581646.218   793.4 1660.69
   827.2 1660.95   840.4 1658.32  857.021670.859   873.5 1683.14   886.8 1684.29
  907.921698.389     953 1726.31   969.6  1730.4   979.5 1740.13    1012 1759.87
#Mann= 9 ,-1 , 0
       0     .12       0     294    .035       0   560.8     .12       0
   570.6     .12       0  737.77    .016       0  767.58     .06       0
   827.2     .08       0  857.02    .016       0  907.92     .12       0
Bank Sta=294,560.8
XS Rating Curve= 0 ,0
Exp/Cntr=0.3,0.1

Type RM Length L Ch R = 1 ,73287   ,550.9,534.8,494.9
XS GIS Cut Line= 3
     2110718.671       262857.84     2111013.467      263410.049
 2111166.1210224263743.882794566
#Sta/Elev= 30
       0 1929.79   104.1 1827.32   115.2 1818.39   133.8 1796.28   163.6 1770.83
   204.5 1730.25   215.7 1716.69   226.8 1698.86     238 1691.93  309.33 1631.97
   318.1 1625.71  337.26 1621.87  511.83 1622.15   539.2 1626.77   561.5 1626.97
   576.4 1632.04   592.9 1641.99  657.24 1645.08  754.681641.819   787.1 1643.98
  800.44 1651.47   809.4 1658.37  819.641659.772  852.121658.955   862.9 1659.76
   884.61676.724   895.4 1683.37   909.8 1684.55  917.081689.571   993.1  1722.7
#Mann= 10 ,-1 , 0
       0     .12       0  309.33    .035       0   576.4     .12       0
  657.24     .06       0  754.68    .016       0  800.44     .06       0
  819.64     .08       0  852.12     .12       0   884.6    .016       0
  917.08     .12       0
Bank Sta=309.33,576.4
XS Rating Curve= 0 ,0
Exp/Cntr=0.3,0.1

Type RM Length L Ch R = 1 ,72752   ,571.5,562.8,523.1
XS GIS Cut Line= 4
     2110231.357      263153.128     2110360.647      263370.297
     2110579.046      263663.9062110783.61731744264010.388634889
#Sta/Elev= 30
       0 1889.24    57.2 1840.45   119.6 1781.98   194.7 1718.54   292.8 1646.15
   303.5 1635.67   318.5 1629.67   341.8 1622.26   472.4 1622.08   542.2 1622.26
   554.5  1630.4   583.1 1641.21  628.181643.322  665.581643.249  686.271642.754
  699.891642.091  744.361640.751   791.3  1644.2  802.451646.861  802.791647.045
   817.9 1657.76   837.11659.369     856 1659.94   871.41656.276   887.5 1664.24
   905.71670.065   920.8 1670.15     940 1678.83   974.1  1691.6    1021  1713.6
#Mann= 14 ,-1 , 0
       0     .12       0   318.5    .035       0   554.5     .12       0
  628.18     .06       0  665.58     .12       0  686.27     .06       0
  699.89     .12       0  744.36    .016       0  802.45     .12       0
  802.79     .06       0   837.1     .08       0   871.4     .12       0
   905.7    .016       0     940     .12       0
Bank Sta=318.5,554.5
XS Rating Curve= 0 ,0
Exp/Cntr=0.3,0.1

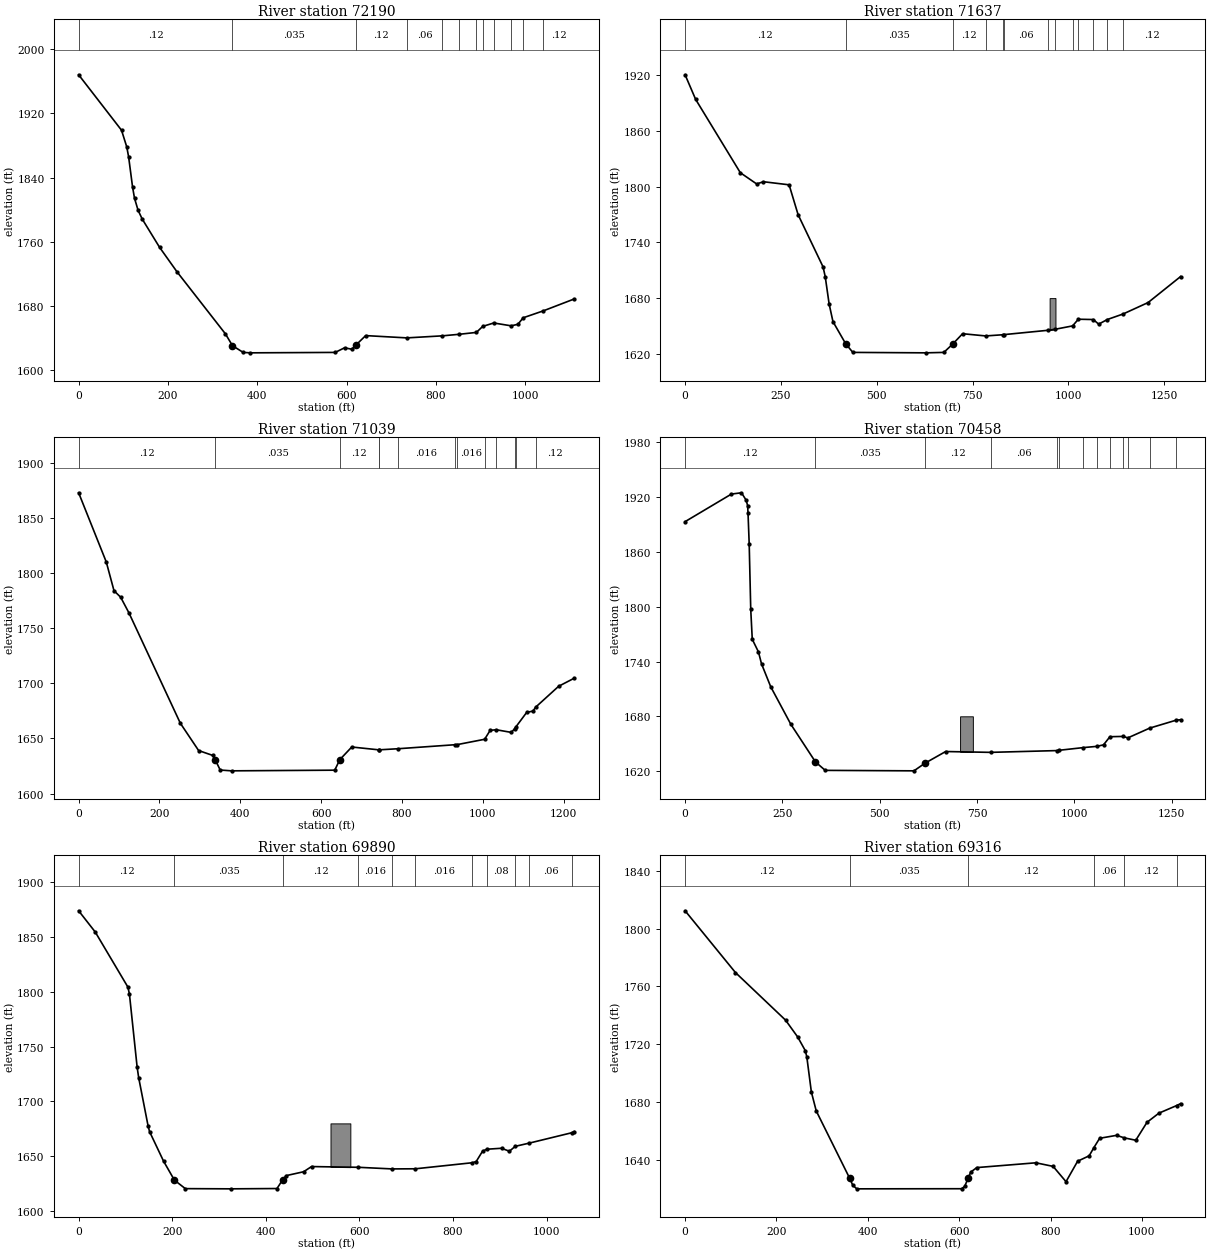
Type RM Length L Ch R = 1 ,72190   ,561.1,552.9,502.3
XS GIS Cut Line= 3
     2109714.898      263512.957     2110181.763      264028.977
2110451.45888513264343.049225928
#Sta/Elev= 30
       0 1968.17    96.1    1899   107.9 1878.01     112 1865.68   120.8 1828.17
   125.2 1814.11   133.2 1799.11   142.5 1788.19   181.2 1753.07   220.3 1722.47
   328.8 1645.06   344.6 1630.31   368.6 1621.94  384.68 1621.41   574.6 1621.94
   595.5 1627.66   611.9 1625.94     621 1631.08   642.9 1642.91  735.091640.061
  814.351642.592   851.91644.512  890.831646.882  905.021654.379  929.771658.635
   968.71655.108   983.9 1657.01  995.691665.127 1041.031673.818  1109.9 1688.57
#Mann= 12 ,-1 , 0
       0     .12       0   344.6    .035       0     621     .12       0
  735.09     .06       0  814.35     .12       0   851.9    .016       0
  890.83     .12       0  905.02     .06       0  929.77     .08       0
   968.7     .12       0  995.69    .016       0 1041.03     .12       0
Bank Sta=344.6,621
XS Rating Curve= 0 ,0
Exp/Cntr=0.3,0.1

Type RM Length L Ch R = 1 ,71637   ,613.7,598,578.3
XS GIS Cut Line= 3
     2109223.535       263929.07     2109522.283      264141.088
2110225.13058818264744.445611533
#Sta/Elev= 30
       0 1920.17    27.5 1893.72   144.1 1814.83   186.6  1802.8   204.5 1805.15
   271.3 1801.84   294.8 1769.68   359.8 1713.64   365.5 1703.17   375.7 1673.71
   385.7 1654.71     419 1630.83   437.6 1621.62  628.07 1621.15   674.9 1621.62
   698.3 1630.69   723.8 1641.72  784.031639.327  829.381640.617  831.121640.714
  947.891645.452  965.431646.514 1010.781650.119 1025.741657.292 1064.671656.966
  1078.8 1652.01 1101.481657.002 1142.521662.935  1207.7 1675.22  1292.6 1703.23
#Mann= 13 ,-1 , 0
       0     .12       0     419    .035       0   698.3     .12       0
  784.03     .06       0  829.38    .016       0  831.12     .06       0
  947.89     .12       0  965.43    .016       0 1010.78     .06       0
 1025.74     .08       0 1064.67     .12       0 1101.48    .016       0
 1142.52     .12       0
#Block Obstruct= 1 ,-1
  950.84   966.1    1680
Bank Sta=419,698.3
XS Rating Curve= 0 ,0
Exp/Cntr=0.3,0.1

Type RM Length L Ch R = 1 ,71039   ,588.4,581,549.5
XS GIS Cut Line= 3
     2108866.175      264411.039     2109231.959      264681.644
2109844.02402049265150.706657291
#Sta/Elev= 30
       0 1872.63    68.4 1809.92    87.5 1783.89     104 1777.96   124.5 1763.77
   251.7 1663.74   296.9 1639.01   331.5 1634.63   338.5 1630.27   350.3 1621.34
  378.46 1620.62   633.7 1621.22   646.2 1630.76   675.8 1642.22  741.971639.684
  744.071639.672  790.531640.661  930.13 1644.26  936.221644.361 1004.551649.223
  1018.2  1657.3 1033.35 1657.86  1070.4 1655.47 1078.981658.829 1081.911660.462
  1108.7 1673.64  1124.3 1674.77 1130.471678.217  1187.7 1697.27  1226.1 1704.55
#Mann= 13 ,-1 , 0
       0     .12       0   338.5    .035       0   646.2     .12       0
  741.97     .06       0  744.07     .12       0  790.53    .016       0
  930.13     .12       0  936.22    .016       0 1004.55     .12       0
 1033.35     .08       0 1078.98     .12       0 1081.91    .016       0
 1130.47     .12       0
Bank Sta=338.5,646.2
XS Rating Curve= 0 ,0
Exp/Cntr=0.3,0.1

Type RM Length L Ch R = 1 ,70458   ,613.9,567.7,401.5
XS GIS Cut Line= 3
     2108512.425      264895.679     2109087.142       265284.56
2109589.26658818265573.793634889
#Sta/Elev= 30
       0 1893.15   119.1 1923.35   144.9 1924.75   156.8  1916.7   160.7  1910.7
   161.7 1902.57   164.7 1868.82   168.7 1796.96   172.6 1764.32   188.5 1750.49
   196.4 1737.43   220.1 1712.29   271.6 1671.35     335 1630.04   360.1  1620.8
  588.08 1620.29   616.3 1628.61   669.6 1641.44  784.921640.522  955.351642.463
  960.071642.745 1023.531645.746 1057.611647.064  1075.2 1648.75  1091.71657.664
 1125.781657.969 1137.621656.347 1193.961667.075 1262.131675.795  1273.4 1676.22
#Mann= 13 ,-1 , 0
       0     .12       0     335    .035       0   616.3     .12       0
  784.92     .06       0  955.35     .12       0  960.07     .06       0
 1023.53     .12       0 1057.61    .016       0  1091.7     .06       0
 1125.78     .08       0 1137.62     .12       0 1193.96     .06       0
 1262.13    .016       0
#Block Obstruct= 1 ,-1
  706.64  739.46    1680
Bank Sta=335,616.3
XS Rating Curve= 0 ,0
Exp/Cntr=0.3,0.1

Type RM Length L Ch R = 1 ,69890   ,571.4,574.1,584.5
XS GIS Cut Line= 4
     2108459.339      265651.682     2108588.754       265669.43
     2108911.184      265719.8252109494.89222497265867.019840324
#Sta/Elev= 30
       0    1874    35.6 1854.56   105.2 1804.43   108.5 1798.26     125 1731.41
   128.3 1721.75   148.3 1677.95   151.6 1672.45   181.5 1645.52   204.7  1628.2
     228 1620.46  325.52 1620.27   423.9 1620.55     436 1628.51   443.8 1632.35
   480.8 1635.86   497.7  1640.6  597.891639.924   669.71638.451  719.741638.567
  841.581644.105   849.6 1645.19   863.1 1654.53  872.051656.408   903.7  1657.3
   920.6 1654.58  932.971659.044  963.431662.038 1054.821671.556    1059 1672.53
#Mann= 11 ,-1 , 0
       0     .12       0   204.7    .035       0     436     .12       0
  597.89    .016       0   669.7     .06       0  719.74    .016       0
  841.58     .12       0  872.05     .08       0  932.97     .12       0
  963.43     .06       0 1054.82    .016       0
#Block Obstruct= 1 ,-1
  538.25  580.69    1680
Bank Sta=204.7,436
XS Rating Curve= 0 ,0
Exp/Cntr=0.3,0.1

Type RM Length L Ch R = 1 ,69316   ,517.8,565.9,616.2
XS GIS Cut Line= 3
       2108244.7      266190.839     2108921.347      266299.209
  2109274.963704266484.947293134
#Sta/Elev= 30
       0 1812.29   110.2 1769.63   219.9 1736.75   246.5 1725.08   263.1 1715.67
   266.4 1711.41   276.4 1687.08   287.1 1673.99   360.4 1627.39   367.3 1622.53
   375.9  1620.2   605.3 1620.28     612 1621.89   619.4 1627.48   625.2 1631.76
   638.5 1634.88   767.9 1638.19   805.6 1635.71   833.8 1625.14   859.2 1639.28
   884.5 1643.02  894.82 1648.68   907.4 1655.12   944.4 1657.15  961.551655.405
   986.5 1653.77  1011.1 1666.17  1037.1 1672.47 1075.661677.691  1084.7 1679.08
#Mann= 6 ,-1 , 0
       0     .12       0   360.4    .035       0   619.4     .12       0
  894.82     .06       0  961.55     .12       0 1075.66     .06       0
Bank Sta=360.4,619.4
XS Rating Curve= 0 ,0
Exp/Cntr=0.3,0.1

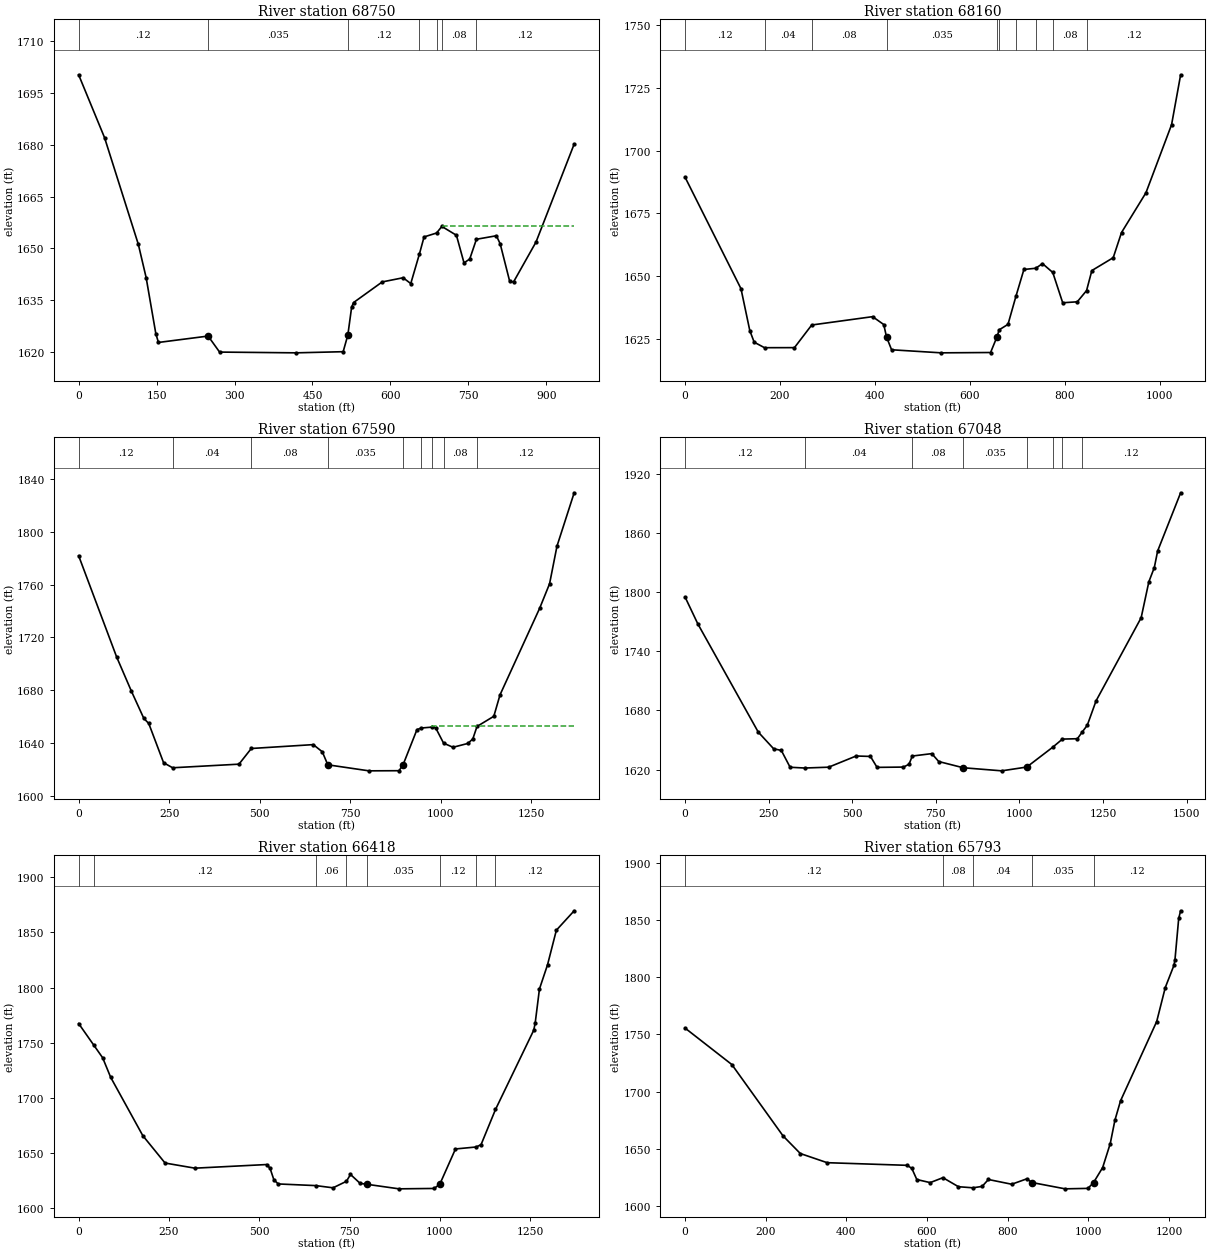
Type RM Length L Ch R = 1 ,68750   ,482.4,590.2,654.3
XS GIS Cut Line= 4
     2108230.148      266630.572     2108410.651      266730.762
      2108730.59      266894.1362109078.26808961267066.365408007
#Sta/Elev= 30
       0 1700.33    49.9  1682.1   114.9 1651.19   129.9 1641.57   148.6 1625.29
   153.6 1622.76   249.2 1624.61   271.3 1619.97  418.33 1619.75   509.1 1620.08
   518.1  1624.9   525.4 1632.98   529.1 1634.32   584.3  1640.3   624.5 1641.51
   639.2 1639.82  655.94 1648.44   664.8 1653.34   688.91654.476  699.021656.383
   727.1 1653.82   741.7 1645.81   752.7 1646.94  765.571652.662     804 1653.68
   811.3 1651.35   829.6 1640.47     837 1640.29   880.3 1651.87   953.7 1680.25
#Mann= 7 ,-1 , 0
       0     .12       0   249.2    .035       0   518.1     .12       0
  655.94     .06       0   688.9     .08       0  699.02     .08       0
  765.57     .12       0
#XS Ineff= 2 , 0
                          700.97         1656.38
Permanent Ineff=
       F       F
Bank Sta=249.2,518.1
XS Rating Curve= 0 ,0
Exp/Cntr=0.3,0.1

Type RM Length L Ch R = 1 ,68160   ,455.4,570.2,625.2
XS GIS Cut Line= 4
     2107919.343      266835.286     2108105.362      267183.657
     2108350.086      267426.843 2108519.5473632267679.007999046
#Sta/Elev= 30
       0 1689.38   117.7 1645.04   136.3 1628.35   145.5 1623.74  167.241621.558
   230.3 1621.58   266.7 1630.59   394.9 1633.91   418.4 1630.77  424.27  1625.8
   434.9 1620.73  539.46 1619.51   643.4 1619.64   656.9 1625.87   661.6 1628.68
   680.1 1630.85  696.68 1641.94   713.6 1652.69  738.581653.179   752.7 1655.02
  774.371651.506   795.3 1639.44     826 1639.82  845.551644.284   856.7 1652.26
   901.7 1657.38   919.2  1667.4   970.6 1683.21  1024.6 1710.31  1043.7 1730.18
#Mann= 10 ,-1 , 0
       0     .12       0  167.24     .04       0   266.7     .08       0
  424.27    .035       0   656.9     .12       0   661.6     .12       0
  696.68     .06       0  738.58     .08       0  774.37     .08       0
  845.55     .12       0
#XS Ineff= 2 , 0
                           750.6          1654.7
Permanent Ineff=
       F       F
Bank Sta=424.27,656.9
XS Rating Curve= 0 ,0
Exp/Cntr=0.3,0.1

Type RM Length L Ch R = 1 ,67590   ,425.7,541.6,571.9
XS GIS Cut Line= 4
2107486.54740896266821.848228791     2107659.811      267431.586
     2107775.647      267721.4272107894.04656768268126.398498569
#Sta/Elev= 30
       0 1781.76   104.9 1705.26   145.8 1679.31   179.9 1658.87   193.6 1654.98
   234.5 1625.34  259.44 1621.53   442.6 1624.25   476.7  1636.1   647.7 1639.02
   672.6 1633.61   687.8 1623.77   801.3 1619.21   884.4 1619.31  895.76 1623.92
   933.9 1650.32   945.81651.568  976.58 1652.27   985.5 1651.74 1007.361640.138
  1033.4 1637.01  1074.4 1639.91  1088.1 1643.31 1099.681652.746  1146.1 1660.43
  1163.3 1676.69  1272.7 1742.09    1300 1760.57  1320.5 1789.04  1367.9 1829.31
#Mann= 9 ,-1 , 0
       0     .12       0  259.44     .04       0   476.7     .08       0
   687.8    .035       0  895.76     .06       0   945.8     .08       0
  976.58     .12       0 1007.36     .08       0 1099.68     .12       0
#XS Ineff= 2 , 0
                          974.16         1653.08
Permanent Ineff=
       F       F
Bank Sta=687.8,895.76
XS Rating Curve= 0 ,0
Exp/Cntr=0.3,0.1

Type RM Length L Ch R = 1 ,67048   ,302.6,629.8,686.4
XS GIS Cut Line= 4
2107167.88854528266802.6206844642107151.52155953267133.325421242
     2107214.836       267867.032107242.68527264268280.751657291
#Sta/Elev= 30
       0 1794.76    38.2 1767.51   218.8 1657.93   264.8 1641.04   287.8 1639.33
   314.1 1622.28  357.88  1621.5   429.3 1622.35   511.6 1633.69   554.4 1633.25
   574.2 1622.16   653.2 1622.47   669.7 1625.33   679.6 1633.65   737.9  1636.1
   758.6 1628.09   831.9 1621.78  947.05 1618.65    1022  1622.5 1099.011642.439
 1128.621650.827  1173.4 1651.21 1187.831658.008    1203 1664.89  1229.3 1689.64
  1364.1 1773.82  1387.1 1810.26  1403.5 1824.73  1413.4 1841.47  1482.2 1900.48
#Mann= 8 ,-1 , 0
       0     .12       0  357.88     .04       0   679.6     .08       0
   831.9    .035       0    1022     .12       0 1099.01     .06       0
 1128.62     .08       0 1187.83     .12       0
Bank Sta=831.9,1022
XS Rating Curve= 0 ,0
Exp/Cntr=0.3,0.1

Type RM Length L Ch R = 1 ,66418   ,418.9,625.6,640.1
XS GIS Cut Line= 3
2107049.79902049266798.307981414       2106691.5      267478.268
     2106357.315      267980.392
#Sta/Elev= 30
       0  1767.5   41.561748.089    66.5 1736.47    88.7 1718.76   177.7 1665.86
   239.3 1641.06   321.9 1636.41   521.1 1639.71     530  1636.2   540.5 1625.88
   552.6 1622.11  656.351620.617   704.3 1618.61   741.4 1624.51   752.6 1630.72
   779.1 1622.67   797.2 1621.84  886.86 1617.68   984.1 1618.03   999.8 1621.85
  1043.2 1653.82 1100.681655.616  1114.1 1657.79 1153.991689.594  1259.9 1761.47
  1263.9    1768  1275.7 1798.83    1298 1820.67  1322.5 1852.07  1371.8 1869.68
#Mann= 8 ,-1 , 0
       0    .016       0   41.56     .12       0  656.35     .06       0
   741.4     .08       0   797.2    .035       0   999.8     .12       0
 1100.68    .016       0 1153.99     .12       0
Bank Sta=797.2,999.8
XS Rating Curve= 0 ,0
Exp/Cntr=0.3,0.1

Type RM Length L Ch R = 1 ,65793   ,360.3,503.7,531.2
XS GIS Cut Line= 4
2106897.59085986266632.963525741     2106211.895      267156.807
     2106001.349      267319.408      2105916.86      267373.275
#Sta/Elev= 30
       0 1755.59     116 1723.64   243.1 1661.04   285.8 1645.66   352.4 1637.63
   551.3 1635.31   562.4 1632.57   574.7 1622.88   607.8 1620.17  639.531624.488
     678 1616.57  713.871615.615   736.7 1616.84   752.3  1622.9   810.1 1618.74
   847.3 1623.45   860.3 1620.25   942.6 1614.71  999.13 1615.11  1013.1 1620.22
  1035.7 1633.38  1054.5 1654.37  1066.1  1674.9  1080.1 1691.92  1169.7 1761.36
    1191 1791.17  1212.4 1810.53    1215 1815.38  1224.3 1851.77  1229.1 1858.44
#Mann= 5 ,-1 , 0
       0     .12       0  639.53     .08       0  713.87     .04       0
   860.3    .035       0  1013.1     .12       0
Bank Sta=860.3,1013.1
XS Rating Curve= 0 ,0
Exp/Cntr=0.3,0.1