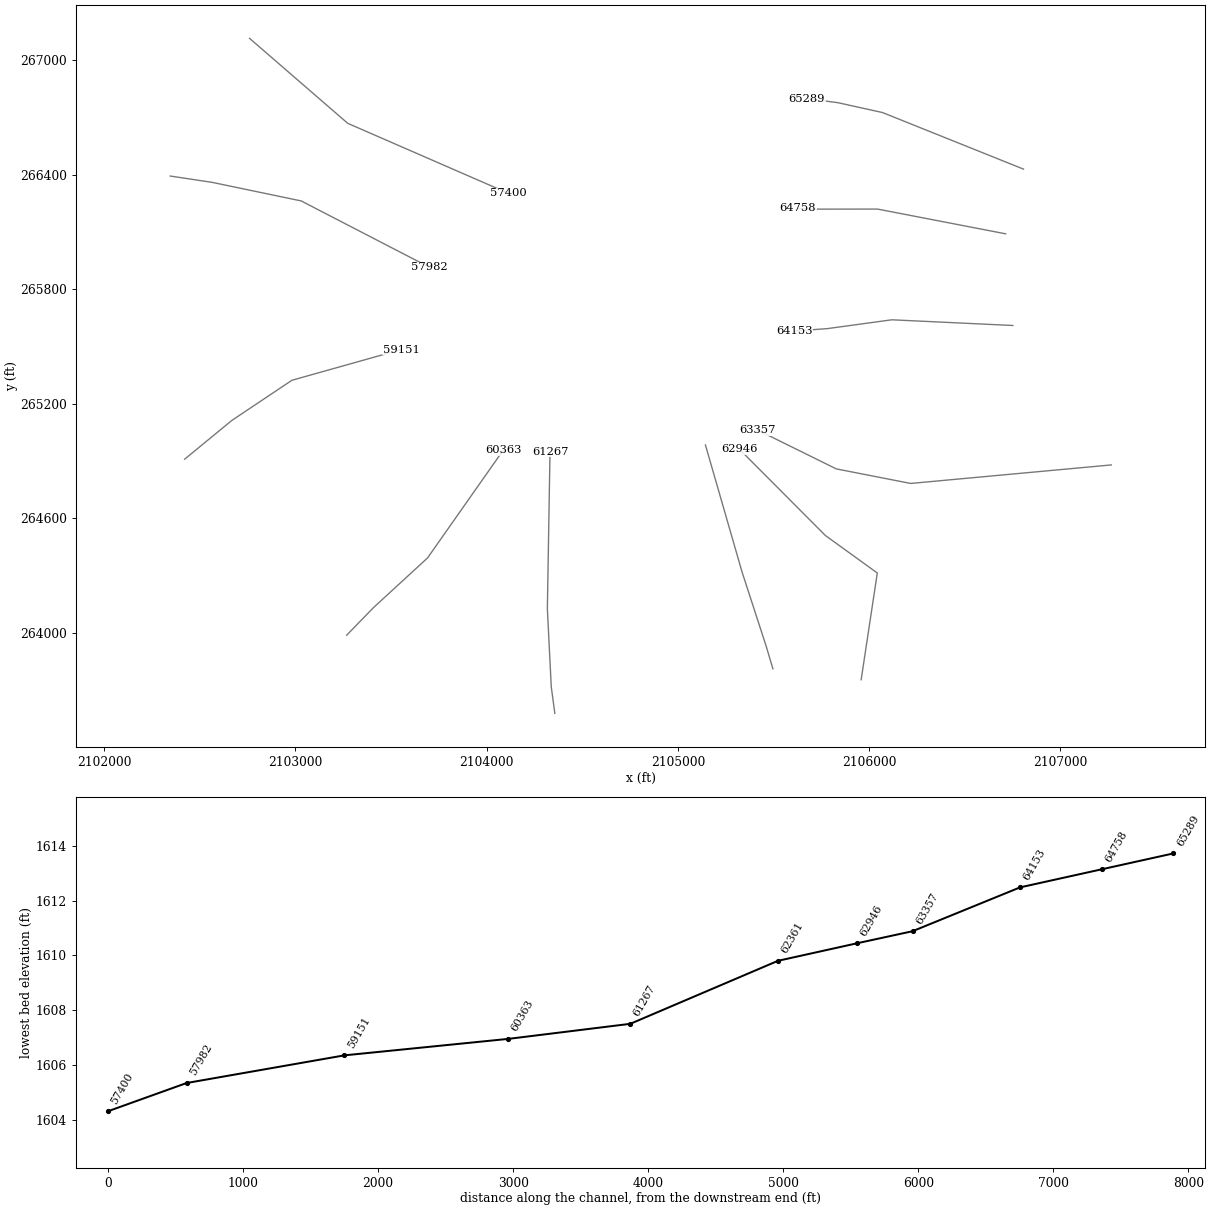
HEC-RAS study GRBRRV3.prj: GRBRRV3

--- GRBRRV3.g01 (geometry) --- (continued)

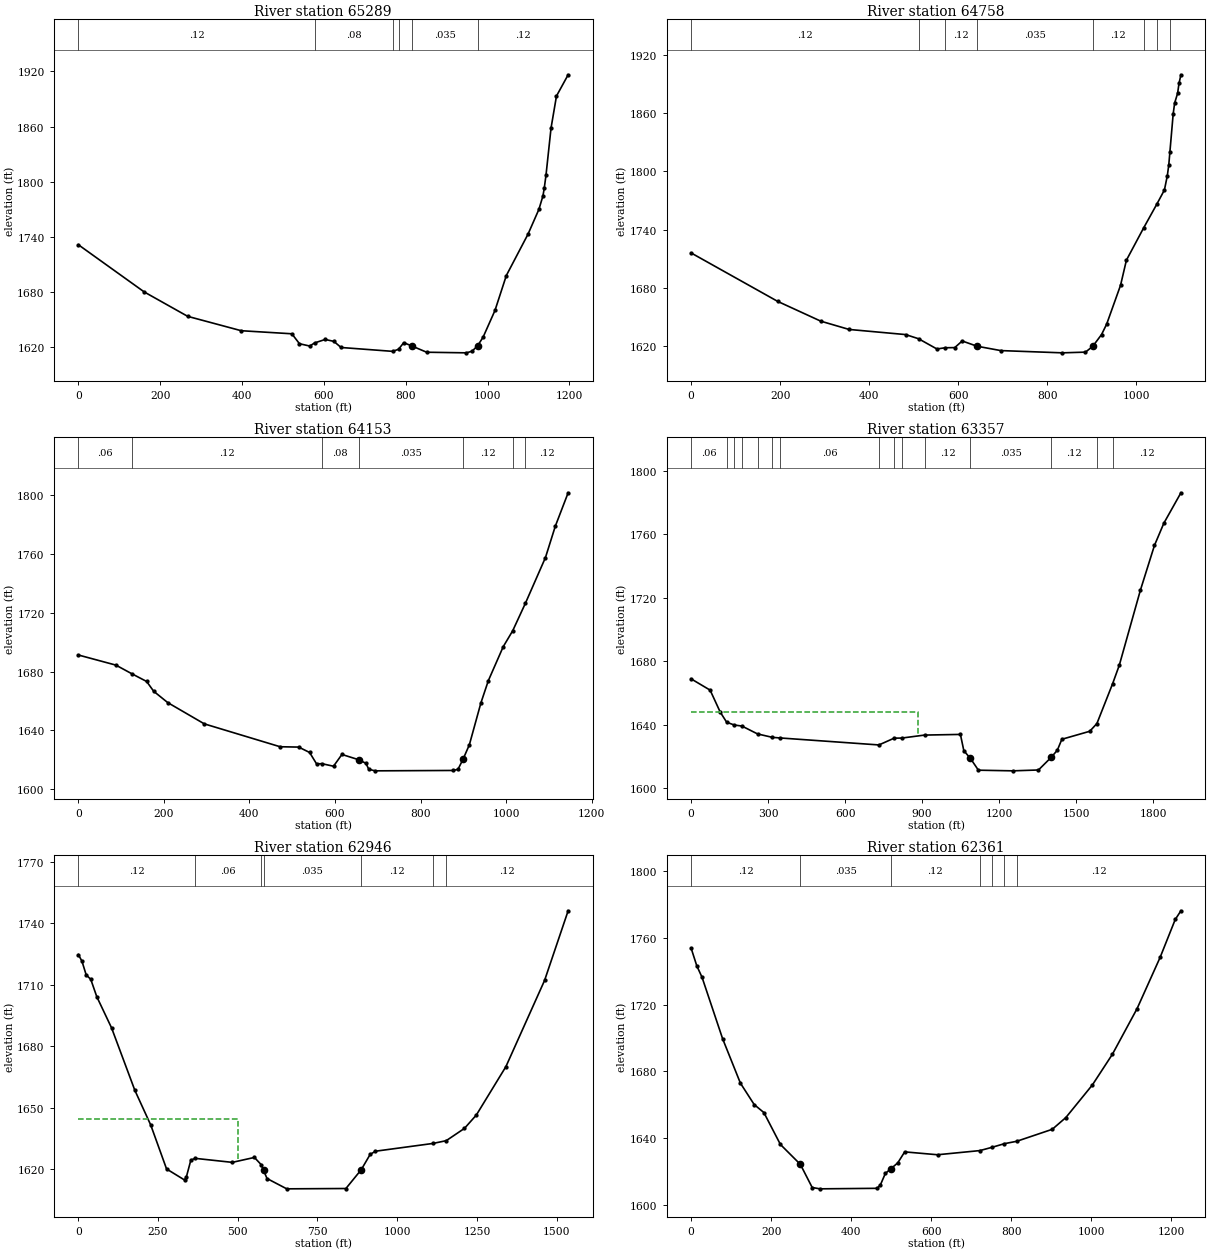
Type RM Length L Ch R = 1 ,65289   ,455.1,531.3,553.7
XS GIS Cut Line= 4
2106806.85942755266428.569456627     2106069.513       266724.75
      2105836.13      266776.377     2105674.353      266797.678
#Sta/Elev= 30
       0 1731.39   161.1 1679.97   267.2 1653.44     398  1637.8   521.7 1634.46
   540.3 1623.64   565.5 1621.11  577.191624.493   603.1 1628.28   624.3  1626.2
     642 1619.54  768.181615.332   782.4 1617.61   795.1 1624.79   814.2 1621.32
   851.1 1614.38  948.31 1613.72     962  1615.5   975.5 1621.37   988.9 1630.69
    1018 1659.83  1045.8  1697.9  1098.8 1742.94  1125.3 1769.83  1135.2 1784.45
  1138.5 1793.08  1142.7 1807.12    1155 1858.36  1168.3 1893.24  1196.8 1916.38
#Mann= 6 ,-1 , 0
       0     .12       0  577.19     .08       0  768.18    .035       0
   782.4     .08       0   814.2    .035       0   975.5     .12       0
Bank Sta=814.2,975.5
XS Rating Curve= 0 ,0
Exp/Cntr=0.3,0.1

Type RM Length L Ch R = 1 ,64758   ,553.7,604.6,618.3
XS GIS Cut Line= 4
2106713.62556482266089.801614395     2106043.631       266219.36
     2105725.831      266219.047     2105626.239      266222.396
#Sta/Elev= 30
       0    1716   194.3 1666.14   291.2 1645.75   354.7 1637.23   481.7 1631.94
   510.71627.664   551.9 1617.13  570.871618.381     592 1618.53   608.7 1625.35
   642.1 1619.95   695.3 1615.46  833.61 1613.14   885.6 1613.87     902  1619.9
   921.7 1632.01   933.1 1642.67   964.3 1682.69   977.5 1708.58 1015.971741.603
 1045.52 1766.04  1062.8 1780.82  1069.4 1795.61  1072.7 1807.02 1075.08 1819.69
  1082.5 1859.16  1085.8 1870.42  1092.4 1880.29  1095.6 1890.59  1099.9 1899.48
#Mann= 8 ,-1 , 0
       0     .12       0   510.7     .08       0  570.87     .12       0
   642.1    .035       0     902     .12       0 1015.97    .016       0
 1045.52     .12       0 1075.08     .06       0
Bank Sta=642.1,902
XS Rating Curve= 0 ,0
Exp/Cntr=0.3,0.1

Type RM Length L Ch R = 1 ,64153   ,844.1,796.1,738.1
XS GIS Cut Line= 4
2106751.28674595265609.881045758      2106118.61      265639.698
     2105782.252      265593.607     2105610.452      265580.782
#Sta/Elev= 30
       0 1691.32    87.8 1684.43  125.661678.458   159.7  1673.3   176.1 1666.65
     209 1658.92   294.6 1644.44   471.7 1628.88   515.2 1628.64   540.7 1624.98
   557.1 1617.17  569.211617.363   596.6 1615.62   616.3 1623.63   655.9    1620
   672.4  1617.6   679.1 1613.52  693.88 1612.48  877.03 1612.74   887.7 1613.54
  899.35  1620.3   914.2 1630.18   941.3 1658.78   958.7 1673.92   993.5 1697.02
  1015.61707.824 1045.221726.489  1092.2 1757.67  1115.2 1778.98  1145.2 1801.72
#Mann= 7 ,-1 , 0
       0     .06       0  125.66     .12       0  569.21     .08       0
   655.9    .035       0  899.35     .12       0  1015.6    .016       0
 1045.22     .12       0
Bank Sta=655.9,899.35
XS Rating Curve= 0 ,0
Exp/Cntr=0.3,0.1

Type RM Length L Ch R = 1 ,63357   ,615.6,411,298.5
XS GIS Cut Line= 4
2107265.81596997264879.878521925     2106216.805      264782.949
     2105827.976      264859.1642105416.63213823 265062.44211201
#Sta/Elev= 30
       0 1668.89      74 1661.78   113.5  1647.9  138.46 1641.54  168.131639.776
  197.791639.135  258.761634.165  316.441632.002   346.11631.626  731.731627.214
  791.051631.486  820.711631.548   909.71633.438  1049.3 1633.85  1062.6 1623.58
 1088.191618.734  1119.4 1611.29 1253.61 1610.88  1353.4 1611.42  1403.6 1619.48
    1427 1623.93  1444.6 1630.79  1553.2 1635.83 1581.151640.725 1642.58 1665.94
  1668.4 1677.52  1750.5 1724.78  1805.4 1753.08    1842 1767.09  1908.5 1786.26
#Mann= 15 ,-1 , 0
       0     .06       0  138.46     .12       0  168.13     .06       0
  197.79     .12       0  258.76     .06       0  316.44    .016       0
   346.1     .06       0  731.73    .016       0  791.05     .12       0
  820.71     .06       0   909.7     .12       0 1088.19    .035       0
  1403.6     .12       0 1581.15    .016       0 1642.58     .12       0
#XS Ineff= 2 , 0
          884.57 1647.77
Permanent Ineff=
       F       F
Bank Sta=1088.19,1403.6
XS Rating Curve= 0 ,0
Exp/Cntr=0.3,0.1

Type RM Length L Ch R = 1 ,62946   ,647.7,585.3,429.2
XS GIS Cut Line= 4
2105958.13247903263755.411935656     2106042.509      264314.069
     2105770.817      264510.6072105322.35093375264961.372679693
#Sta/Elev= 30
       0 1724.67    11.3 1721.46    24.6 1714.77      39 1712.59    57.8 1704.15
   104.2 1688.93   177.2 1658.49     227 1641.58   276.7 1620.13     333 1614.76
   338.8 1616.24   352.8 1624.41  366.281625.308   482.9 1623.35   552.2 1625.75
  574.161622.118   580.8  1619.5   591.7 1615.48   653.6 1610.44   839.2  1610.6
   887.3 1619.78   915.2 1627.22   931.9 1628.79 1111.971632.573 1153.851633.929
    1211 1639.92  1248.2 1646.42    1341 1670.04  1462.2 1712.04  1536.2 1746.04
#Mann= 7 ,-1 , 0
       0     .12       0  366.28     .06       0  574.16     .12       0
   580.8    .035       0   887.3     .12       0 1111.97    .016       0
 1153.85     .12       0
#XS Ineff= 2 , 0
          500.54 1644.54
Permanent Ineff=
       F       F
Bank Sta=580.8,887.3
XS Rating Curve= 0 ,0
Exp/Cntr=0.3,0.1

Type RM Length L Ch R = 1 ,62361   ,1122.1,1093.7,1014.7
XS GIS Cut Line= 4
     2105496.696      263812.622     2105460.705      263933.565
     2105335.973      264317.3792105143.89754624  264984.3610877
#Sta/Elev= 30
       0 1753.76    14.1 1743.22    27.3 1736.31    78.6 1699.63   123.1 1673.03
   157.6  1660.2   181.8 1655.42   223.1 1636.34   272.9 1624.44   302.5  1610.6
  321.86  1609.8   464.6 1610.11  472.59 1611.97   485.3 1619.02   499.4 1621.87
   516.4 1625.37   533.6 1631.91   615.6 1630.19  721.391632.679  752.131634.663
  782.871636.819  813.611638.246   902.3 1645.41   936.3 1652.45  1002.6 1671.96
  1052.5 1690.26  1114.2 1717.57  1171.7 1748.18  1209.6 1770.92  1223.8 1776.12
#Mann= 7 ,-1 , 0
       0     .12       0   272.9    .035       0   499.4     .12       0
  721.39    .016       0  752.13     .12       0  782.87     .06       0
  813.61     .12       0
Bank Sta=272.9,499.4
XS Rating Curve= 0 ,0
Exp/Cntr=0.3,0.1

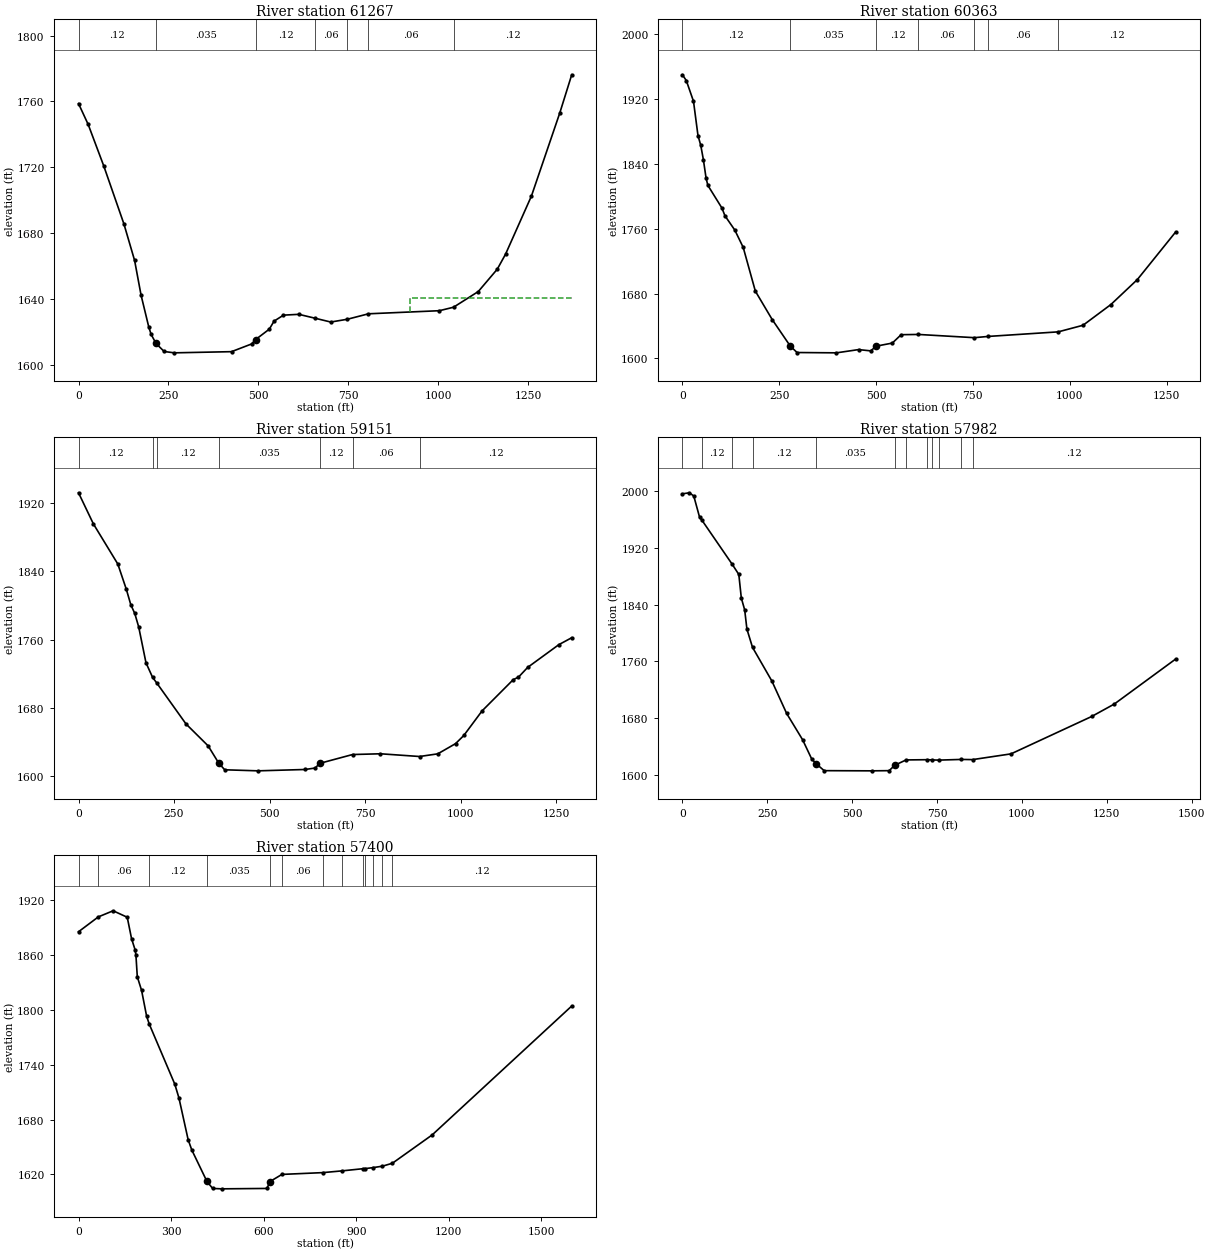
Type RM Length L Ch R = 1 ,61267   ,980.6,904.2,650.4
XS GIS Cut Line= 4
     2104356.547      263579.191     2104337.865      263718.283
     2104317.449      264126.9182104331.34320448264948.150494753
#Sta/Elev= 30
       0 1758.72    26.9 1746.04    69.9 1721.04   126.2  1685.7   155.9 1663.54
   173.9 1642.44   195.3 1623.15   201.8  1618.7   215.4 1613.19     238 1608.32
  266.13  1607.5   425.2 1608.21   481.1 1612.89     492 1615.52   530.3 1621.87
   543.5 1626.74   569.7 1630.37   612.4 1630.86  658.231628.458     701 1626.19
  746.851627.858  805.941631.185  1002.9 1633.06 1042.27 1635.17  1111.1 1644.69
  1163.8 1658.23  1186.9 1667.36  1258.8 1702.61  1337.6 1753.02  1370.8 1776.19
#Mann= 7 ,-1 , 0
       0     .12       0   215.4    .035       0     492     .12       0
  658.23     .06       0  746.85    .016       0  805.94     .06       0
 1042.27     .12       0
#XS Ineff= 2 , 0
                          920.53         1640.93
Permanent Ineff=
       F       F
Bank Sta=215.4,492
XS Rating Curve= 0 ,0
Exp/Cntr=0.3,0.1

Type RM Length L Ch R = 1 ,60363   ,1222.4,1211.7,1165.4
XS GIS Cut Line= 4
     2103268.326      263988.559     2103408.569      264133.089
     2103690.991      264392.8712104086.31308865264956.455200664
#Sta/Elev= 30
       0 1949.81      10 1942.73    28.6 1917.14    40.2 1874.82    47.3 1862.92
    54.1 1845.28    61.1  1822.3    65.7 1813.43   102.1 1785.41   109.8 1775.98
   135.3  1758.3     157 1736.91   188.3 1683.04   231.9 1647.92   278.7 1615.18
     296 1607.34  397.76 1606.95   454.8 1610.95   485.9 1609.39   501.1 1615.26
     542    1619   564.8 1629.32  609.51 1629.62  753.831625.646  789.91  1627.2
  970.311632.817  1034.4 1640.95  1106.3 1666.49  1174.6 1697.26  1273.5 1755.93
#Mann= 7 ,-1 , 0
       0     .12       0   278.7    .035       0   501.1     .12       0
  609.51     .06       0  753.83    .016       0  789.91     .06       0
  970.31     .12       0
Bank Sta=278.7,501.1
XS Rating Curve= 0 ,0
Exp/Cntr=0.3,0.1

Type RM Length L Ch R = 1 ,59151   ,1223,1168.9,929
XS GIS Cut Line= 4
     2102421.026       264909.93     2102668.378      265113.264
     2102981.779       265323.022103553.34879266265483.878181124
#Sta/Elev= 30
       0  1931.7      39 1895.23   102.9 1848.32   125.3 1818.56   136.9 1800.69
   147.3 1790.46   157.6 1774.64   176.6 1732.82  193.911715.691  204.72 1709.21
   281.3 1661.26   339.3 1635.58     367 1615.44   382.7 1607.58  469.94 1606.35
   593.1 1607.93   619.6 1609.66   631.5 1615.11  717.411625.433   790.4 1626.31
  892.751623.124   940.4 1626.23     987 1638.18  1008.6 1647.71  1056.3 1676.42
  1138.1 1713.09  1151.7 1715.97  1175.8  1727.4  1257.4    1754  1291.1 1762.11
#Mann= 7 ,-1 , 0
       0     .12       0  193.91     .06       0  204.72     .12       0
     367    .035       0   631.5     .12       0  717.41     .06       0
  892.75     .12       0
Bank Sta=367,631.5
XS Rating Curve= 0 ,0
Exp/Cntr=0.3,0.1

Type RM Length L Ch R = 1 ,57982   ,627.3,582,482.5
XS GIS Cut Line= 4
     2102345.433      266392.342     2102564.398      266359.299
     2103030.385      266262.0082103701.01522307265914.601684464
#Sta/Elev= 30
       0  1996.7    20.8 1998.16    33.5 1993.49    50.7 1963.38   57.081959.699
   146.71897.116   166.1 1882.82   173.5 1849.48   183.4 1832.73     190 1805.56
  206.441779.816   263.5 1732.22     307 1686.43   354.1  1649.2   380.8 1622.12
   394.2 1615.22   417.6  1605.6   557.8 1605.34   609.1  1605.6   625.4 1613.25
  658.91 1620.75  721.491621.081  736.361620.754  754.761620.489  821.291621.461
  854.561621.193   967.9 1629.31  1205.5 1682.12  1272.1 1699.69  1452.8 1763.24
#Mann= 12 ,-1 , 0
       0     .06       0   57.08     .12       0   146.7     .06       0
  206.44     .12       0   394.2    .035       0   625.4     .12       0
  658.91     .06       0  721.49     .12       0  736.36     .06       0
  754.76     .12       0  821.29    .016       0  854.56     .12       0
Bank Sta=394.2,625.4
XS Rating Curve= 0 ,0
Exp/Cntr=0.3,0.1

Type RM Length L Ch R = 1 ,57400   ,1062.8,1073.3,1066.4
XS GIS Cut Line= 3
     2102760.261      267113.219     2103273.995      266668.069
2104115.98815395 266300.92295615
#Sta/Elev= 30
       0 1884.95   64.23  1901.2   112.2 1907.86   157.9 1900.79   171.9 1877.39
   183.5 1865.08     186 1859.65   190.5 1835.84   204.4 1820.91   220.7 1792.82
  229.251784.146   311.9 1718.69   325.4 1703.58   355.3  1657.9   367.2 1646.66
  416.22 1612.36   434.7 1604.74  463.81 1604.31   610.7 1604.74   620.7 1612.31
  659.191620.063   791.71622.013  853.58 1623.91  920.59 1626.25  927.471626.329
  952.82  1627.4  985.041629.048 1017.261632.281    1146 1663.16  1598.3 1803.89
#Mann= 13 ,-1 , 0
       0     .12       0   64.23     .06       0  229.25     .12       0
  416.22    .035       0   620.7     .12       0  659.19     .06       0
   791.7    .016       0  853.58     .06       0  920.59     .12       0
  927.47     .08       0  952.82     .12       0  985.04     .08       0
 1017.26     .12       0
Bank Sta=416.22,620.7
XS Rating Curve= 0 ,0
Exp/Cntr=0.3,0.1