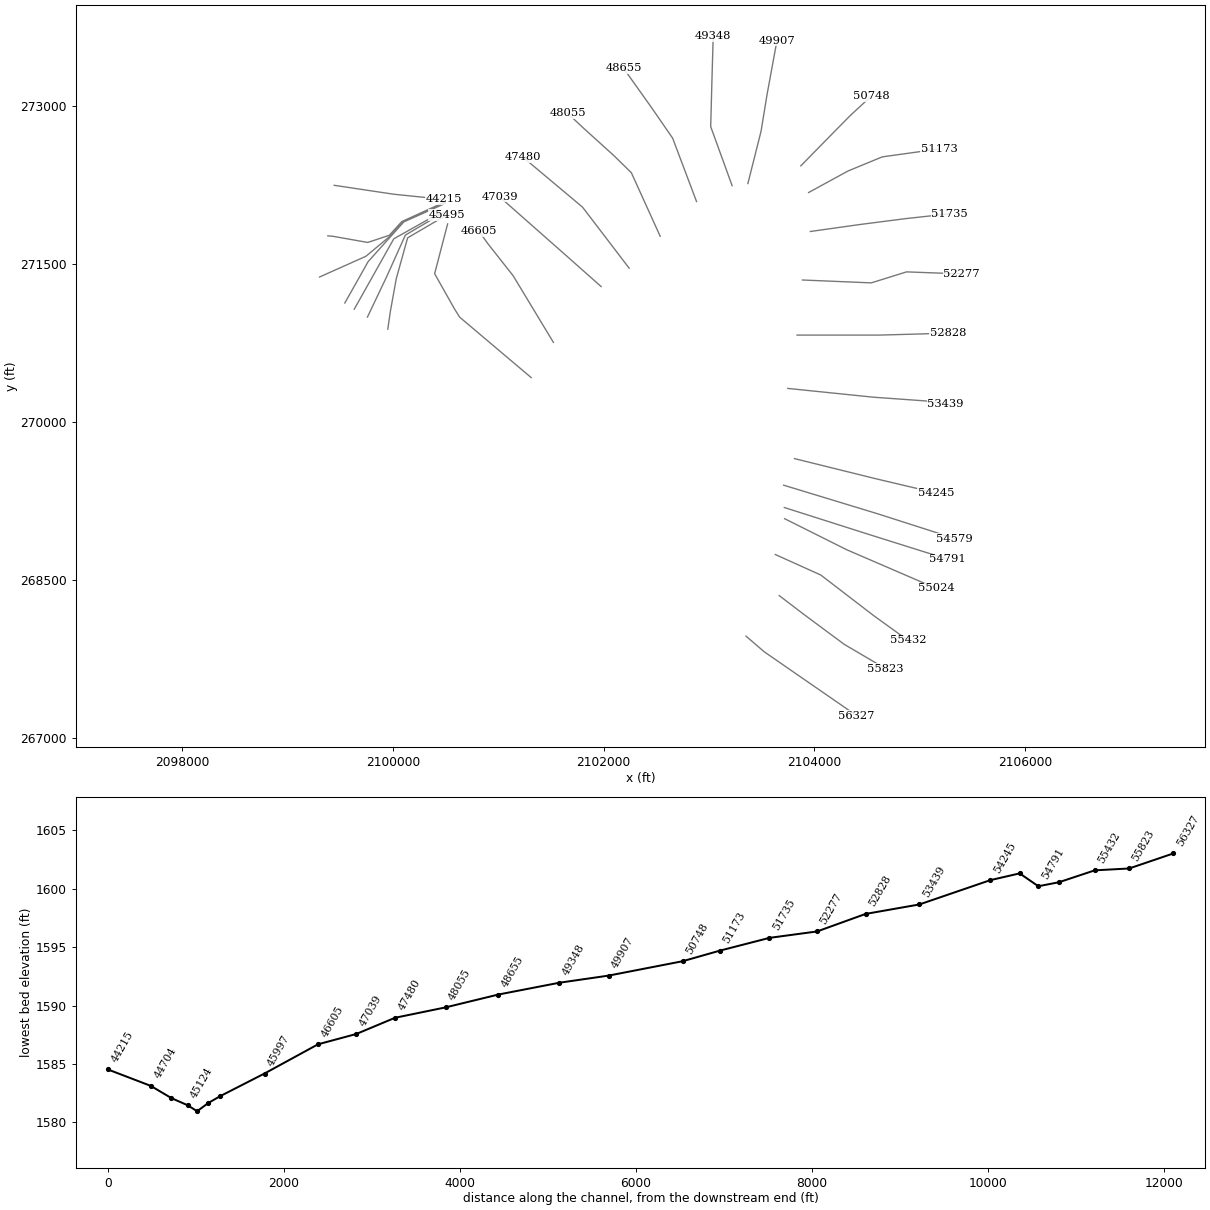
HEC-RAS study GRBRRV3.prj: GRBRRV3

--- GRBRRV3.g01 (geometry) --- (continued)

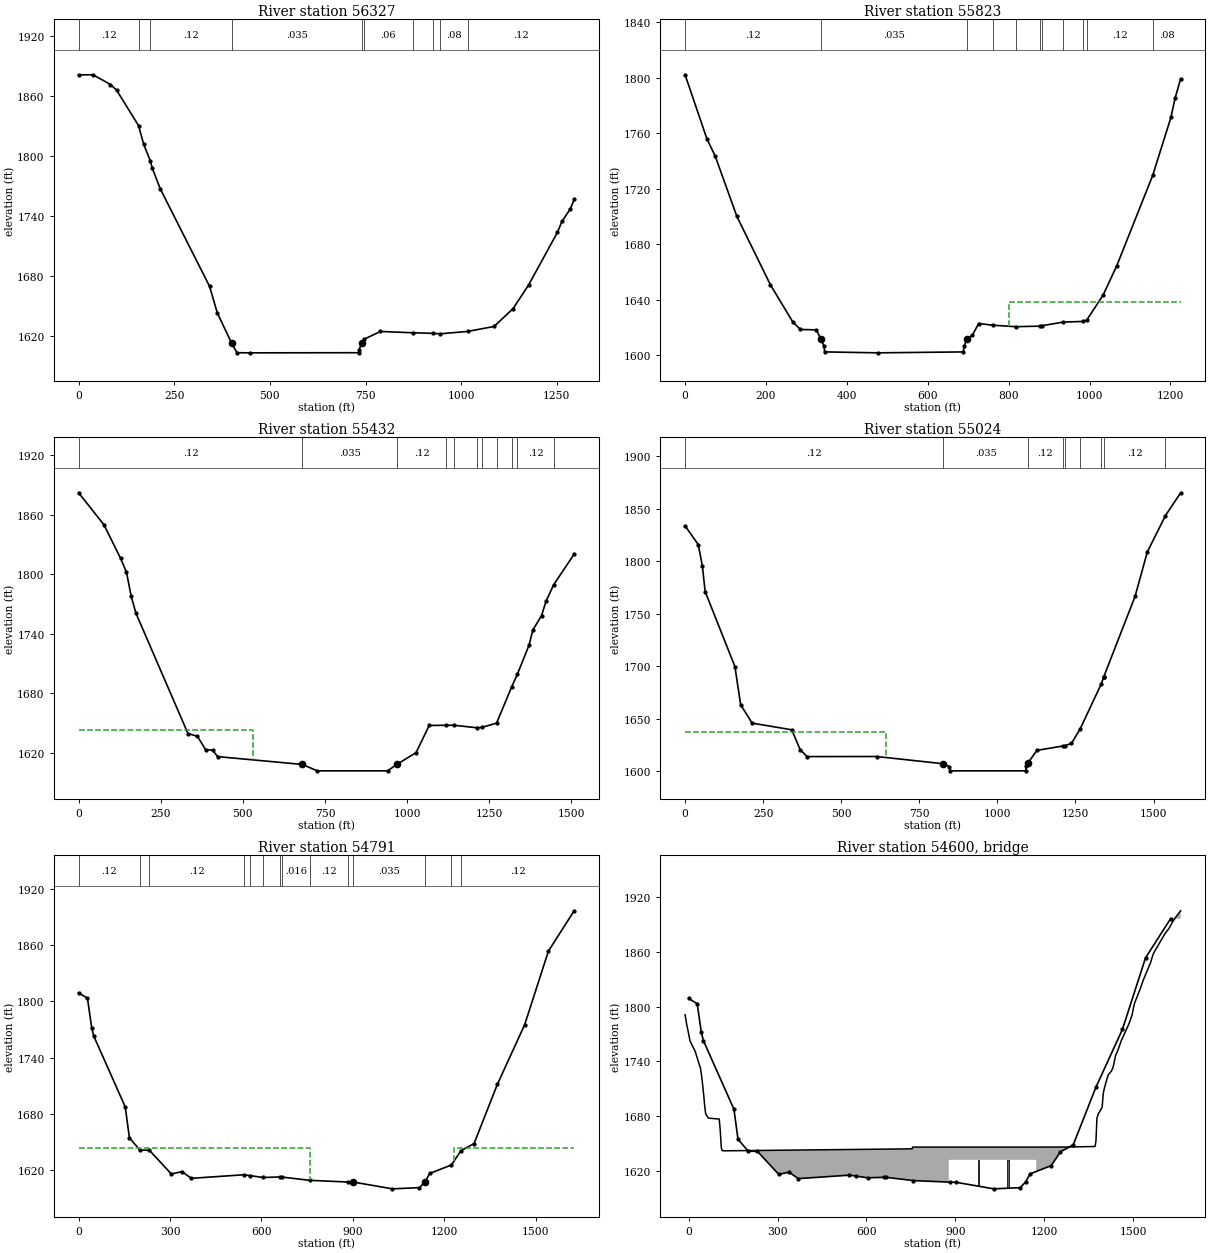
Type RM Length L Ch R = 1 ,56327   ,508.5,503.4,490.9
XS GIS Cut Line= 3
     2103352.382      267970.784     2103525.953      267821.711
2104403.43197474267215.481547189
#Sta/Elev= 30
       0  1881.2    37.5 1881.27    83.3 1871.53    99.6 1865.68  156.67 1830.37
   170.2 1811.54  187.581794.926   192.6 1787.68   213.7  1766.9   342.3 1669.55
   362.2 1643.29   399.7 1612.81   413.8 1603.16  447.92 1603.03   732.2 1603.16
   733.1 1606.31  740.03 1612.47     745 1616.41   788.7 1624.43  873.581623.112
  925.541622.543  944.751622.106 1016.551624.425    1086 1629.44  1135.5 1647.25
  1176.3 1671.03  1251.5 1723.56  1263.4 1734.62  1285.1 1746.94  1295.3 1756.55
#Mann= 10 ,-1 , 0
       0     .12       0  156.67     .06       0  187.58     .12       0
   399.7    .035       0  740.03     .12       0     745     .06       0
  873.58    .016       0  925.54     .12       0  944.75     .08       0
 1016.55     .12       0
Bank Sta=399.7,740.03
XS Rating Curve= 0 ,0
Exp/Cntr=0.3,0.1

Type RM Length L Ch R = 1 ,55823   ,396.6,391,387.6
XS GIS Cut Line= 4
     2103668.286      268355.251     2103903.227      268175.983
     2104285.314      267892.5312104676.68674785267662.537774072
#Sta/Elev= 30
       0 1802.13    53.9 1755.96    74.6  1743.4     128 1700.07   210.8 1650.84
   266.1 1624.07     285 1618.59   324.7 1618.28  335.56 1611.65   343.5 1606.62
     345 1602.41  477.44 1601.74   688.2 1602.41   689.6 1606.55   697.4 1611.75
     710 1614.31   725.8 1622.87  761.621621.631  818.21 1620.58  876.511620.985
  882.03 1621.26   934.81623.906  984.821624.374   993.11625.367  1033.5 1643.36
  1067.5 1664.64 1156.12  1729.6  1201.3 1771.53  1211.3 1785.12  1225.2 1799.15
#Mann= 11 ,-1 , 0
       0     .12       0  335.56    .035       0   697.4     .12       0
  761.62     .06       0  818.21     .12       0  876.51     .08       0
  882.03    .016       0   934.8     .12       0  984.82     .08       0
   993.1     .12       0 1156.12     .08       0
#XS Ineff= 2 , 0
                          800.43         1638.23
Permanent Ineff=
       F       F
Bank Sta=335.56,697.4
XS Rating Curve= 0 ,0
Exp/Cntr=0.3,0.1

Type RM Length L Ch R = 1 ,55432   ,359.9,408.1,456.2
XS GIS Cut Line= 4
2103630.85349624268745.3573387192104062.90134017268550.581671376
2104560.88960093 268168.113088232104890.76875389267930.026395221
#Sta/Elev= 30
       0 1881.91    77.3 1849.54   127.7  1815.8   145.7 1801.88   160.1 1777.43
   174.5 1760.49   332.8  1639.2   361.6 1636.41   386.8 1622.87   408.4 1622.45
   422.8 1615.94   681.3 1608.01   726.5 1601.58   940.5 1601.58   970.3 1608.35
  1027.4 1619.99  1067.3 1647.32  1117.3 1647.52  1142.3 1647.54  1211.7 1645.05
  1227.3 1645.38  1272.4 1649.67  1318.2 1686.09  1335.9 1699.09  1371.1 1728.13
  1382.9 1743.59  1409.4 1758.04  1422.8 1772.46  1446.3 1789.14  1508.7 1820.14
#Mann= 11 ,-1 , 0
       0     .12       0   681.3    .035       0   970.3     .12       0
  1117.3     .06       0  1142.3     .12       0  1211.7     .08       0
  1227.3    .016       0  1272.4     .12       0  1318.2     .08       0
  1335.9     .12       0  1446.3     .08       0
#XS Ineff= 2 , 0
          531.61 1642.27
Permanent Ineff=
       F       F
Bank Sta=681.3,970.3
XS Rating Curve= 0 ,0
Exp/Cntr(USF)=0,0
Exp/Cntr=0.3,0.1

Type RM Length L Ch R = 1 ,55024   ,212.4,233.5,251
XS GIS Cut Line= 3
2103719.38789049269085.3294126272104307.25626829268791.395223728
2105160.72782883268423.092143661
#Sta/Elev= 30
       0 1833.86    42.2    1816    55.4 1795.52    64.2 1771.31   159.5 1699.89
   177.9  1663.5   214.6 1646.01   341.5 1639.63   368.6 1620.68   390.6 1614.13
   612.9 1614.21   826.3 1607.34   846.51604.644   847.8 1600.56  1090.7 1600.56
  1091.3 1604.77  1097.9    1608  1126.5 1620.05  1208.7 1624.15  1215.8 1624.46
  1237.2 1626.67  1265.4 1640.74  1332.7 1683.35  1340.9 1690.24  1340.9 1690.26
  1340.9 1690.29  1440.9 1766.71  1480.2 1809.12  1538.1 1843.59  1586.8 1865.37
#Mann= 9 ,-1 , 0
       0     .12       0   826.3    .035       0  1097.9     .12       0
  1208.7     .08       0  1215.8    .016       0  1265.4     .12       0
  1332.7     .08       0  1340.9     .12       0  1538.1     .08       0
#XS Ineff= 2 , 0
          644.47 1637.39
Permanent Ineff=
       F       F
Bank Sta=826.3,1097.9
XS Rating Curve= 0 ,0
Exp/Cntr(USF)=0,0
Exp/Cntr=0.5,0.3

Type RM Length L Ch R = 1 ,54791   ,218.6,211.6,210.7
XS GIS Cut Line= 3
     2103716.339      269191.571     2104522.203      268935.032
     2105267.002      268700.874
#Sta/Elev= 30
       0 1808.93      29 1803.16    42.8 1771.86    49.9  1762.7     153 1687.44
   166.7 1654.55  201.291641.473  232.291641.281   304.4    1616   338.9 1618.56
   369.9 1611.41  542.271615.207  563.291614.303  604.271612.316  660.651612.848
  666.271612.818  758.011609.281  883.211607.508     901 1607.47 1030.09 1600.22
  1118.8  1601.5  1137.3 1607.76  1152.2 1616.62 1223.81 1625.65 1254.771640.794
    1298 1648.47  1374.6 1711.63  1464.1 1775.04  1542.1 1853.47  1626.5  1896.3
#Mann= 14 ,-1 , 0
       0     .12       0  201.29    .016       0  232.29     .12       0
  542.27    .016       0  563.29     .12       0  604.27    .016       0
  660.65     .12       0  666.27    .016       0  758.01     .12       0
  883.21     .06       0     901    .035       0  1137.3     .12       0
 1223.81    .016       0 1254.77     .12       0
#XS Ineff= 2 , 0
          758.86 1643.29    1233            1644
Permanent Ineff=
       F       F
Bank Sta=901,1137.3
XS Rating Curve= 0 ,0
Exp/Cntr=0.5,0.3

Type RM Length L Ch R = 3 ,54600   ,,,
BEGIN DESCRIPTION:
Railroad Crossing
Survey Data not available
Structure data obtained from FIS profile plot
US and DS crosssection lowered based on FIS profile
Deck is 14 ft based on FIS
The length of the opening measured from topo to be 300 ft approximately
END DESCRIPTION:
Bridge Culvert--1,0,-1,-1, 0
Deck Dist Width WeirC Skew NumUp NumDn MinLoCord MaxHiCord MaxSubmerge Is_Ogee
60,30,2.6,0, 60, 60, , , 0.98, 0, 0,0,,
 -11.885  -5.785  -2.285   4.715  22.315  36.315  39.915  43.415  46.915  51.315
  53.915  57.415  64.515  68.015 103.115 104.615 106.615 110.215 112.215 113.715
 122.315 745.715 754.515 755.615 778.515     878    11731272.6151371.2151372.515
1374.7151375.1151377.6151378.2151382.8151395.6151399.1151402.5151413.0151416.515
1426.9151430.4151433.9151440.8151449.7151459.9151486.0151496.5151503.4151506.915
1524.3151534.1151559.1151566.0151569.5151607.8151621.7151632.1151642.7151660.515
 1791.04    1779 1774.02 1762.42 1750.74 1735.97 1732.94 1724.91 1715.45 1701.82
 1692.18 1682.58  1678.8 1677.68 1676.74 1672.26 1664.74 1645.68  1643.1 1642.03
 1641.91 1644.04 1644.14    1646    1646    1646    1646 1646.06 1646.63 1647.94
 1652.93 1655.39 1674.84 1677.98 1682.53 1689.56 1704.04 1709.92 1722.04 1725.26
 1729.37 1731.66  1735.5 1746.26 1753.06 1762.44 1781.08 1790.72 1801.94 1805.33
 1819.71 1828.87 1848.21 1855.81 1858.74 1880.12 1885.91  1892.2 1897.48 1905.04
                                                                                
                                                                                
                                            1632    1632
                                                                                
                                                                                
                                                                                
       0    85.7    91.8    95.3   102.3   119.9   133.9   137.5     141   144.5
   148.9   151.5     155   162.1   165.6   200.7   202.2   204.2   207.8   211.3
   219.9   786.8     794   805.5   876.1     935    1230  1370.2  1468.8  1470.1
  1472.3  1472.7  1475.2  1475.8  1480.4  1493.2  1496.7  1500.1  1510.6  1514.1
  1524.5    1528  1531.5  1538.4  1547.3  1557.5  1583.6  1594.1    1601  1604.5
  1621.9  1631.7  1656.7  1663.6  1667.1  1705.4  1719.3  1729.7  1740.3  1758.1
 1791.04 1791.04    1779 1774.02 1762.42 1750.74 1735.97 1732.94 1724.91 1715.45
 1701.82 1692.18 1682.58  1678.8 1677.68 1676.74 1672.26 1664.74 1645.68 1642.03
 1641.91 1643.85    1644    1646    1646    1646    1646 1646.06 1646.63 1647.94
 1652.93 1655.39 1674.84 1677.98 1682.53 1689.56 1704.04 1709.92 1722.04 1725.26
 1729.37 1731.66  1735.5 1746.26 1753.06 1762.44 1781.08 1790.72 1801.94 1805.33
 1819.71 1828.87 1848.21 1855.81 1858.74 1880.12 1885.91  1892.2 1897.48 1905.04
                                                                                
                                                                                
                                            1632    1632
                                                                                
                                                                                
                                                                                
Pier Skew, UpSta & Num, DnSta & Num=  ,978, 2 ,1035, 2 , 0 , 0 , 0 ,,
       6       6
    1600    1635
       6       6
    1600    1635
Pier Skew, UpSta & Num, DnSta & Num=  ,1078, 2 ,1135, 2 , 0 , 0 , 0 ,,
       6       6
    1600    1635
       6       6
    1600    1635
BR Coef=-1 , 1 , 0 ,, 0 ,,,0.8,-1,1.2,0,
WSPro=,,,, 1 ,,,, 0 ,,,, 0 ,,,,-1 ,-1 ,-1 , 0 , 0 , 0 , 0 , 0
BC Design=,, 0 ,, 0 ,,,,,,
BC Use User HTab Curves=0
BC User HTab FreeFlow(D)= 0

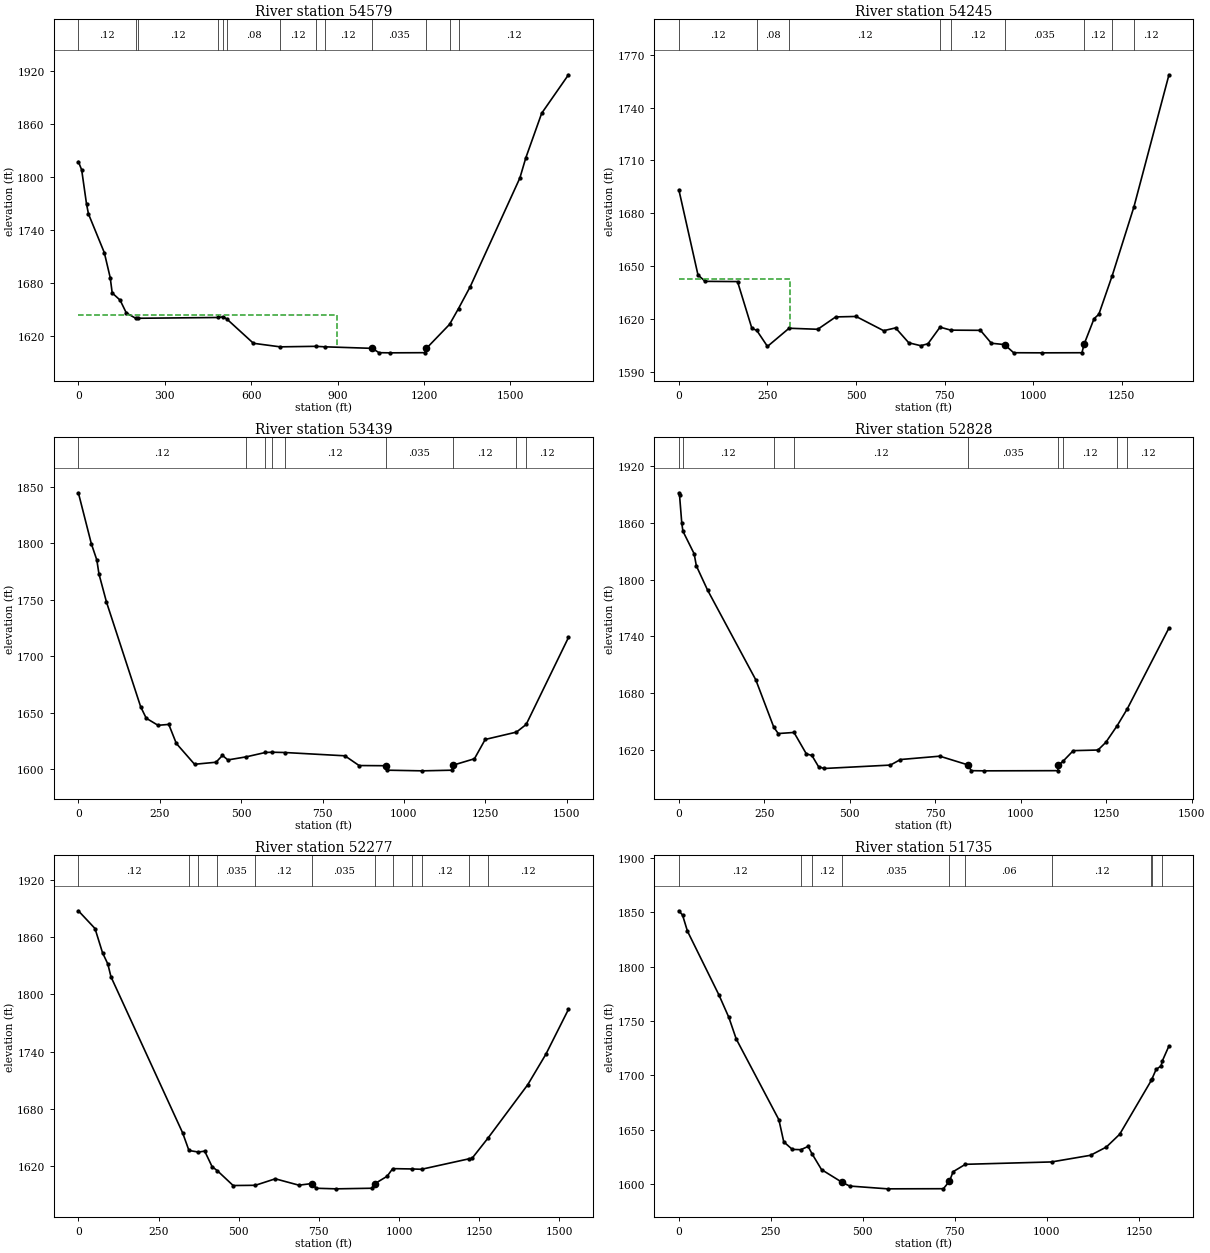
Type RM Length L Ch R = 1 ,54579   ,325.6,334.2,344.2
XS GIS Cut Line= 3
     2103710.302      269403.413     2104595.849      269134.149
     2105335.193      268897.263
#Sta/Elev= 30
       0  1817.8    11.5 1808.51    28.3 1769.94    35.2 1758.53    90.1 1714.79
   110.6 1686.49   117.5 1669.14   144.9 1661.01   166.6 1646.46  198.741640.538
  206.781640.463  484.631641.337  503.291642.126  515.511639.622   607.9 1612.13
  700.741608.103  824.241608.704  855.11 1608.15  1020.5  1606.4  1043.9  1601.5
 1081.74 1601.32  1202.4  1601.5  1208.4  1606.3 1289.021633.579 1320.041651.464
  1360.9 1676.34  1533.1 1799.25  1553.8 1822.17  1608.9 1872.61  1701.9 1916.17
#Mann= 13 ,-1 , 0
       0     .12       0  198.74     .06       0  206.78     .12       0
  484.63     .08       0  503.29     .12       0  515.51     .08       0
  700.74     .12       0  824.24    .016       0  855.11     .12       0
  1020.5    .035       0  1208.4     .12       0 1289.02    .016       0
 1320.04     .12       0
#XS Ineff= 2 , 0
          899.82    1644    1350            1644
Permanent Ineff=
       F       F
Bank Sta=1020.5,1208.4
XS Rating Curve= 0 ,0
Exp/Cntr=0.8,0.6

Type RM Length L Ch R = 1 ,54245   ,763.6,806.1,832.6
XS GIS Cut Line= 4
     2103812.904      269655.898     2104592.073      269463.008
     2104966.962      269374.599      2105155.76      269324.671
#Sta/Elev= 30
       0 1693.36      54 1644.97    74.3 1641.34   165.6 1641.21   206.1 1614.64
  219.811613.501   250.1 1604.38   311.11614.709     392 1614.12   442.7 1621.14
   500.2  1621.4   577.9 1613.33   611.7  1614.9   648.9 1606.44   682.7 1604.79
     703 1605.89  737.111615.329  767.541613.632   851.2 1613.52   881.9 1606.19
  919.371605.428   944.8  1600.8 1026.01 1600.74  1137.6  1600.8 1143.74 1605.67
  1171.8 1620.13  1185.3 1622.64 1223.091644.599 1284.19 1683.55  1383.2 1758.66
#Mann= 9 ,-1 , 0
       0     .12       0  219.81     .08       0   311.1     .12       0
  737.11    .016       0  767.54     .12       0  919.37    .035       0
 1143.74     .12       0 1223.09    .016       0 1284.19     .12       0
#XS Ineff= 2 , 0
             315 1642.82
Permanent Ineff=
       F       F
Bank Sta=919.37,1143.74
XS Rating Curve= 0 ,0
Exp/Cntr=0.3,0.1

Type RM Length L Ch R = 1 ,53439   ,583.4,610.6,628.4
XS GIS Cut Line= 4
2103749.86322974270322.038158722     2104563.275      270238.688
     2105051.519      270203.799     2105247.839      270177.331
#Sta/Elev= 30
       0 1844.83    39.8 1799.78    56.7 1785.36    63.3 1772.93    86.4 1748.07
   191.4 1655.37   208.5 1645.23   244.7 1638.97   277.7 1639.76   300.8 1622.95
   356.9 1604.47   422.8 1606.28   442.6 1612.33   459.1 1608.32  515.361611.036
  574.741614.939  596.071615.129  634.131614.889   818.6 1611.97   862.2 1603.35
   943.6 1603.19   948.5 1599.23 1056.92 1598.66  1147.5 1599.23  1150.8 1603.67
  1216.5 1609.35  1249.5 1626.44 1345.571632.963 1375.381639.719  1505.3 1716.72
#Mann= 9 ,-1 , 0
       0     .12       0  515.36    .016       0  574.74     .12       0
  596.07    .016       0  634.13     .12       0   943.6    .035       0
  1150.8     .12       0 1345.57    .016       0 1375.38     .12       0
Bank Sta=943.6,1150.8
XS Rating Curve= 0 ,0
Exp/Cntr=0.3,0.1

Type RM Length L Ch R = 1 ,52828   ,500.9,551.6,588.7
XS GIS Cut Line= 4
2103837.10066206 270828.45520448     2104620.553      270828.427
     2105008.509      270839.125     2105270.439      270848.358
#Sta/Elev= 30
       0 1891.83       2  1889.3     8.6 1859.55   11.891851.224    44.7 1827.37
    51.2 1814.55      84 1788.94   225.1 1694.03  277.721643.959   290.7 1637.28
   336.81638.436   372.8 1615.85   389.2 1614.08   408.8 1602.13   425.2 1600.34
   618.8 1603.94   648.3 1609.81   763.2 1613.35  846.33 1604.06   855.1 1598.04
  892.12 1597.85  1108.4 1598.04  1110.4 1603.87  1123.2  1607.8  1153.7  1619.2
    1226 1619.85  1248.9 1627.97 1282.211645.625 1311.761663.452  1433.6 1748.86
#Mann= 9 ,-1 , 0
       0     .06       0   11.89     .12       0  277.72    .016       0
   336.8     .12       0  846.33    .035       0  1110.4     .12       0
  1123.2     .12       0 1282.21    .016       0 1311.76     .12       0
Bank Sta=846.33,1110.4
XS Rating Curve= 0 ,0
Exp/Cntr=0.3,0.1

Type RM Length L Ch R = 1 ,52277   ,547.8,541.6,518.7
XS GIS Cut Line= 4
2103888.44195806271351.320794566     2104541.456      271324.056
      2104876.95      271428.5062105399.69583842271408.943682555
#Sta/Elev= 30
       0 1887.45    51.9 1868.86    75.4 1843.46    91.8 1831.82   101.7 1818.32
     325 1655.04   344.81636.516  374.371634.837   393.9 1635.84   416.9 1619.62
  433.491615.274   482.6 1599.82  551.741600.055     614 1606.85   687.7 1600.17
   728.9 1601.93   741.1 1596.97   803.3 1596.35   914.5 1596.97   924.5 1601.76
   962.6  1609.5  980.111617.499 1040.331617.159 1069.891616.826 1217.681627.767
  1227.1 1628.14  1276.8 1649.31  1401.1 1705.35  1457.6 1737.24  1528.1 1784.29
#Mann= 12 ,-1 , 0
       0     .12       0   344.8    .016       0  374.37     .12       0
  433.49    .035       0  551.74     .12       0   728.9    .035       0
   924.5     .12       0  980.11    .016       0 1040.33     .06       0
 1069.89     .12       0 1217.68    .016       0  1276.8     .12       0
Bank Sta=728.9,924.5
XS Rating Curve= 0 ,0
Exp/Cntr=0.3,0.1

Type RM Length L Ch R = 1 ,51735   ,492,561.8,626.9
XS GIS Cut Line= 4
2103963.70318494271811.869636797     2104428.717      271877.452
2104872.83360292271934.5902867932105284.58479266271979.571090562
#Sta/Elev= 30
       0 1851.39      10 1847.47    23.3 1832.71   108.9 1774.01   135.9 1753.34
   155.8 1733.61   271.8  1659.3     285    1639   308.2 1632.06  331.541631.786
   351.3  1634.8  361.371628.265   387.7 1613.46   444.1 1601.66   464.1 1598.37
  567.23  1595.8   718.7 1595.92   735.2 1602.77   745.1 1611.54  778.481618.343
 1012.671620.528  1118.5 1626.64  1161.4 1634.21  1197.7 1645.97 1283.91 1695.65
 1284.791696.357  1296.7 1705.58  1309.9 1708.68 1313.631713.415  1331.6 1727.16
#Mann= 10 ,-1 , 0
       0     .12       0  331.54    .016       0  361.37     .12       0
   444.1    .035       0   735.2     .12       0  778.48     .06       0
 1012.67     .12       0 1283.91    .016       0 1284.79     .12       0
 1313.63    .016       0
Bank Sta=444.1,735.2
XS Rating Curve= 0 ,0
Exp/Cntr=0.3,0.1

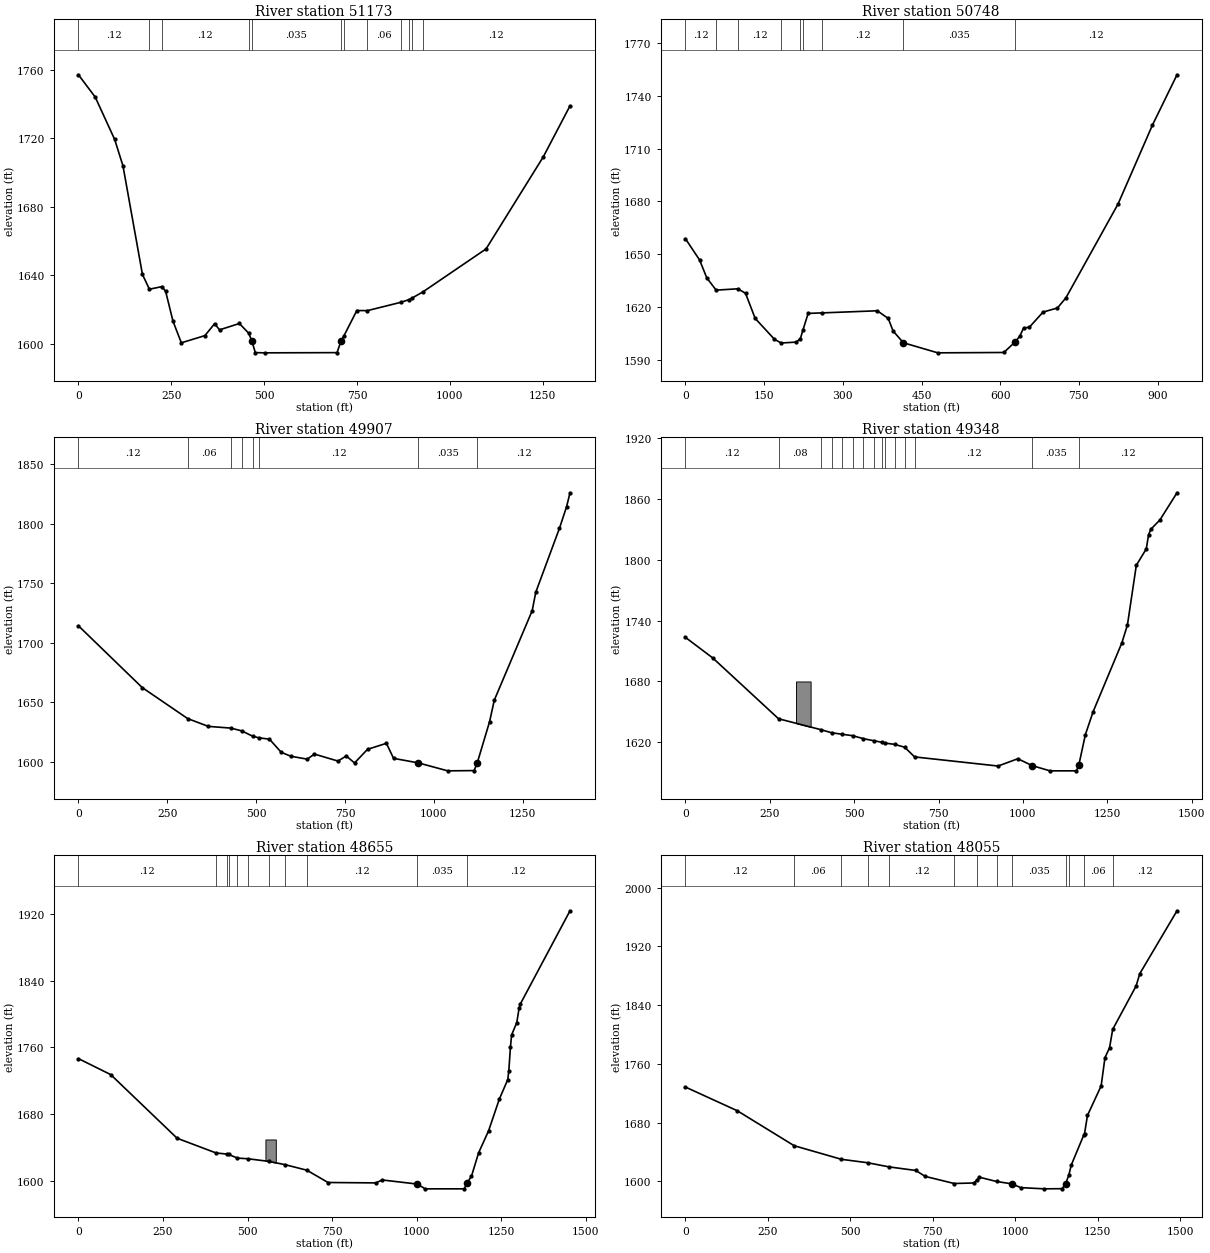
Type RM Length L Ch R = 1 ,51173   ,323.2,425.4,494.2
XS GIS Cut Line= 4
2103947.12716063272181.812660153     2104320.513      272385.904
     2104645.855      272520.1762105186.57306625272595.367545281
#Sta/Elev= 30
       0 1757.14    45.2 1744.11    97.5 1719.39   119.9 1703.94   172.3 1640.52
  191.031631.883  224.691633.389   234.8 1630.62   254.5 1613.24     277 1600.56
   340.5 1604.78   366.7 1611.75   379.8 1608.13   433.3 1611.85  458.551606.138
  467.01 1601.54   476.2 1594.83  502.31 1594.71   696.2 1594.83   706.9 1601.56
  714.181604.407   749.5 1619.42  778.051619.369  867.511624.203  890.011625.785
  897.331626.602  927.151630.276  1097.4 1655.42  1251.5 1709.22  1323.4 1738.99
#Mann= 12 ,-1 , 0
       0     .12       0  191.03    .016       0  224.69     .12       0
  458.55     .06       0  467.01    .035       0   706.9     .12       0
  714.18     .12       0  778.05     .06       0  867.51     .08       0
  890.01     .06       0  897.33     .08       0  927.15     .12       0
Bank Sta=467.01,706.9
XS Rating Curve= 0 ,0
Exp/Cntr=0.3,0.1

Type RM Length L Ch R = 1 ,50748   ,572.4,840.7,877.7
XS GIS Cut Line= 4
     2103872.977      272434.756     2104121.173      272688.217
     2104345.409      272915.553     2104538.577      273093.975
#Sta/Elev= 30
       0 1658.74      27 1646.62    40.7 1636.44   58.511629.484   99.85 1630.23
   114.5 1627.71   132.9 1613.41   169.6 1601.53  182.531599.386   210.9 1599.91
  218.891601.667  223.881606.678   233.9 1616.25  261.111616.534   365.7 1617.73
   386.6 1613.36   395.8 1606.22   415.6 1599.51  481.08  1593.8     607    1594
   627.8 1599.86   637.1 1603.18   644.5 1607.86   655.7 1608.41   681.6 1616.99
   709.1 1619.33   725.3 1625.14   824.5 1678.42   890.1 1723.35     937 1752.01
#Mann= 9 ,-1 , 0
       0     .12       0   58.51    .016       0   99.85     .12       0
  182.53    .016       0  218.89     .12       0  223.88    .016       0
  261.11     .12       0   415.6    .035       0   627.8     .12       0
Bank Sta=415.6,627.8
XS Rating Curve= 0 ,0
Exp/Cntr=0.3,0.1

Type RM Length L Ch R = 1 ,49907   ,497.1,559.5,567.5
XS GIS Cut Line= 4
2103370.41872831272267.0902764572103495.57834268272764.290938359
     2103552.143      273110.663     2103646.079      273621.857
#Sta/Elev= 30
       0 1714.42   179.4 1662.55  307.35 1636.48   365.5 1629.92  429.19 1628.46
  459.65 1626.12  490.111621.677  508.061620.304   537.6 1619.17   570.5 1608.19
   597.5 1604.86     644 1602.37   663.9 1606.66   730.4 1600.78   753.7 1605.08
     777 1599.19   813.5 1610.63   866.7  1615.7   886.8 1603.06   956.8 1599.23
 1039.15 1592.57  1113.6 1592.78 1122.59 1599.49  1156.9 1633.71  1170.3 1651.92
    1277 1727.17    1287 1742.57  1353.8 1796.43  1373.8 1814.53  1383.4 1826.17
#Mann= 8 ,-1 , 0
       0     .12       0  307.35     .06       0  429.19    .016       0
  459.65     .08       0  490.11     .06       0  508.06     .12       0
   956.8    .035       0 1122.59     .12       0
Bank Sta=956.8,1122.59
XS Rating Curve= 0 ,0
Exp/Cntr=0.3,0.1

Type RM Length L Ch R = 1 ,49348   ,430.3,692.8,723.5
XS GIS Cut Line= 4
2103220.81379361272246.7379590122103017.36471065272807.330165242
     2103026.909      273163.304     2103041.126      273667.368
#Sta/Elev= 30
       0 1723.43    81.4 1703.03  275.871643.266  401.561632.495  432.981629.492
   464.41627.997  495.821626.553  527.241623.662  558.661621.588  583.241620.036
  590.091619.347  620.011618.026  649.561615.242   679.11605.673   926.5 1596.69
   984.9 1603.87  1027.8 1597.06  1080.1 1591.96  1158.8 1591.96 1165.66 1597.56
  1185.1 1627.58  1208.1 1650.24  1293.4 1718.12  1309.8 1735.72  1336.1 1794.45
  1365.6  1810.6  1372.3 1824.22  1378.7 1829.78  1406.1 1839.15  1456.7 1865.87
#Mann= 15 ,-1 , 0
       0     .12       0  275.87     .08       0  401.56     .06       0
  432.98    .016       0   464.4     .08       0  495.82     .06       0
  527.24     .12       0  558.66     .08       0  583.24     .12       0
  590.09     .06       0  620.01     .08       0  649.56     .06       0
   679.1     .12       0  1027.8    .035       0 1165.66     .12       0
#Block Obstruct= 1 ,-1
  327.63  370.97    1680
Bank Sta=1027.8,1165.66
XS Rating Curve= 0 ,0
Exp/Cntr=0.3,0.1

Type RM Length L Ch R = 1 ,48655   ,530.8,599.8,617.1
XS GIS Cut Line= 4
2102883.03170305272095.8990729312102656.31341847272697.341029876
     2102454.237      272990.257     2102190.426      273360.971
#Sta/Elev= 30
       0 1746.68    95.4 1727.59   291.8 1651.46  406.751633.884  438.31 1632.54
  443.821632.175  469.881627.758  501.441626.912  564.58 1623.71  611.32 1619.82
  675.251613.275     738 1598.53   879.5 1598.05   898.4 1601.56  1002.2 1596.65
  1025.3 1590.95    1141 1590.95    1148 1597.36  1162.2 1606.04  1183.3    1634
    1213 1660.54  1244.5 1698.17  1269.6 1721.68  1272.7 1732.48  1277.4  1760.3
  1280.9 1774.98  1296.2 1789.85  1303.1 1807.22  1307.1 1812.34  1453.6 1923.51
#Mann= 11 ,-1 , 0
       0     .12       0  406.75     .08       0  438.31     .12       0
  443.82     .08       0  469.88    .016       0  501.44     .12       0
  564.58     .08       0  611.32     .06       0  675.25     .12       0
  1002.2    .035       0    1148     .12       0
#Block Obstruct= 1 ,-1
  552.95  583.64    1650
Bank Sta=1002.2,1148
XS Rating Curve= 0 ,0
Exp/Cntr=0.3,0.1

Type RM Length L Ch R = 1 ,48055   ,568.1,575.2,577.2
XS GIS Cut Line= 5
2102537.88840705271766.6529823682102264.17824021272369.764691937
     2102094.795      272535.471     2101810.727      272792.121
     2101658.757      272935.059
#Sta/Elev= 30
       0 1728.43     157 1696.21   329.81648.546  472.761630.079  552.451625.377
  617.32 1619.74   698.7 1614.84   726.8 1606.82  814.911597.113   875.1 1597.84
  883.321601.691   891.3 1605.68  943.441599.871   991.2 1596.52  1016.7 1591.52
 1088.14 1589.85  1142.2 1590.08  1152.8 1596.62 1162.571608.531    1170 1622.21
 1207.781662.914  1210.2 1664.85  1219.1 1689.73  1260.6    1730  1272.2 1768.44
  1286.2 1782.01  1295.61806.916  1366.5 1865.88  1377.9 1882.87  1490.7 1968.41
#Mann= 13 ,-1 , 0
       0     .12       0   329.8     .06       0  472.76    .016       0
  552.45     .06       0  617.32     .12       0  814.91     .04       0
  883.32     .12       0  943.44     .08       0   991.2    .035       0
  1152.8     .08       0 1162.57     .12       0 1207.78     .06       0
  1295.6     .12       0
Bank Sta=991.2,1152.8
XS Rating Curve= 0 ,0
Exp/Cntr=0.3,0.1

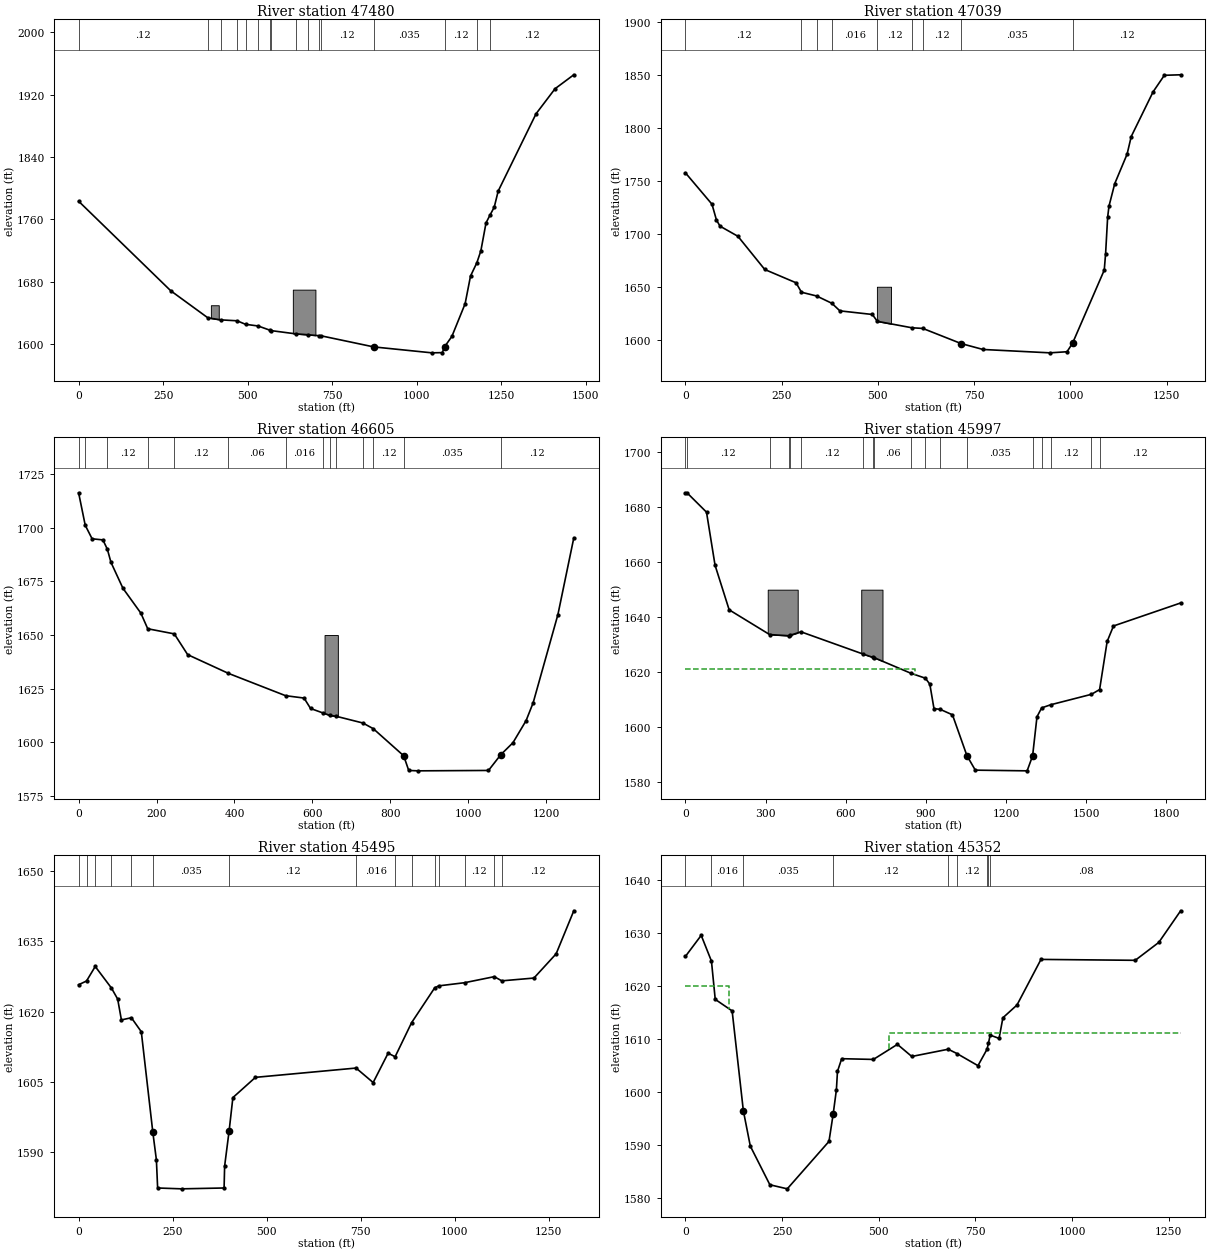
Type RM Length L Ch R = 1 ,47480   ,439.6,441,440.9
XS GIS Cut Line= 3
 2102243.1947245271463.682526695     2101800.588      272043.215
     2101236.578      272516.109
#Sta/Elev= 30
       0 1783.38   272.6 1668.55  382.381633.872  420.311631.235  468.981630.054
  493.871625.541  531.041623.401  566.311617.944   568.21617.536  642.531613.304
   679.71612.118  712.321610.883  716.861610.845   873.3 1596.56 1045.28 1588.96
  1076.1 1589.24    1083 1596.74    1083 1596.82  1104.5 1610.06  1143.6 1651.89
  1159.6 1687.41  1178.41704.497  1190.2 1719.73  1205.5 1755.61 1216.95 1765.31
  1229.8 1775.75  1241.5  1796.4  1353.6 1895.56  1409.8 1927.64  1465.2  1945.5
#Mann= 16 ,-1 , 0
       0     .12       0  382.38     .08       0  420.31    .016       0
  468.98     .06       0  493.87    .016       0  531.04     .06       0
  566.31    .016       0   568.2     .12       0  642.53     .06       0
   679.7     .12       0  712.32     .06       0  716.86     .12       0
   873.3    .035       0    1083     .12       0  1178.4     .06       0
 1216.95     .12       0
#Block Obstruct= 2 ,-1
  391.38   414.7    1650  633.87  700.68    1670
Bank Sta=873.3,1083
XS Rating Curve= 0 ,0
Exp/Cntr=0.3,0.1

Type RM Length L Ch R = 1 ,47039   ,484.6,433.9,413.5
XS GIS Cut Line= 3
2101977.26386348271289.1062205592101680.75760914271552.019381171
2101013.14555369272141.064706459
#Sta/Elev= 30
       0 1757.55    68.9 1727.93    80.5 1713.02    89.8 1707.21   136.3 1697.65
     206 1666.29   287.3 1653.74  301.33 1644.82  340.81 1641.26  380.291634.384
   401.2 1627.22   485.5 1623.81   498.51617.338  588.111611.252  616.681610.624
   716.2 1596.33   773.1 1590.75  946.78 1587.57   991.3  1588.6  1005.6 1596.57
  1088.1 1665.73  1091.6 1681.32  1096.9 1715.76  1100.4 1726.16  1115.3 1747.36
  1147.4  1775.2  1158.2 1791.91    1215 1834.11  1244.2 1849.72  1286.6 1850.21
#Mann= 9 ,-1 , 0
       0     .12       0  301.33    .016       0  340.81     .12       0
  380.29    .016       0   498.5     .12       0  588.11     .06       0
  616.68     .12       0   716.2    .035       0  1005.6     .12       0
#Block Obstruct= 1 ,-1
  497.39  534.12    1650
Bank Sta=716.2,1005.6
XS Rating Curve= 0 ,0
Exp/Cntr=0.3,0.1

Type RM Length L Ch R = 1 ,46605   ,645,608,604.7
XS GIS Cut Line= 4
2101524.32265634 270759.15707293     2101142.306      271391.502
      2100902.84      271695.248     2100818.234       271813.11
#Sta/Elev= 30
       0 1716.32   16.991701.167    34.6 1694.87    62.4 1694.35   73.821689.963
      83  1683.9   113.7 1671.81   159.7 1660.22  177.35 1652.93   245.5 1650.54
   279.8 1640.86   384.4 1632.13  531.131621.723   578.5 1620.62   595.2 1615.76
  625.951613.745  645.391612.504  660.461612.151  729.481608.989   756.21606.335
   834.2 1593.71   847.1 1586.87  870.57 1586.69  1051.8 1586.87  1083.3 1594.21
  1114.5 1599.78  1148.2 1610.07  1166.4 1618.41  1229.9 1659.51  1270.7 1695.29
#Mann= 14 ,-1 , 0
       0     .12       0   16.99    .016       0   73.82     .12       0
  177.35    .016       0   245.5     .12       0   384.4     .06       0
  531.13    .016       0  625.95     .12       0  645.39     .08       0
  660.46     .12       0  729.48     .06       0   756.2     .12       0
   834.2    .035       0  1083.3     .12       0
#Block Obstruct= 1 ,-1
  631.11  665.26    1650
Bank Sta=834.2,1083.3
XS Rating Curve= 0 ,0
Exp/Cntr=0.3,0.1

Type RM Length L Ch R = 1 ,45997   ,596.5,501.8,398.6
XS GIS Cut Line= 5
 2101313.1254714270425.117527649     2100634.148      270998.723
     2100585.051      271077.279     2100396.802      271411.192
2100519.99542235271883.778211539
#Sta/Elev= 30
       0 1685.135.6700441685.19478.69995 1678.16   110.7 1658.88   163.5 1642.68
  315.021633.688  386.641633.265  392.361633.454  432.411634.684  663.041626.669
  701.711625.387  707.021625.257  844.321619.608  897.791617.843   914.5 1615.67
     930  1606.8  953.531606.514   999.2 1604.54  1053.4 1589.69  1084.7 1584.44
 1278.65 1584.19  1299.11589.619  1315.5 1603.83 1333.011607.055  1366.71608.192
 1519.331611.988 1549.851613.715  1578.1 1631.18  1601.8 1636.81  1853.2 1645.17
#Mann= 18 ,-1 , 0
       0    .016       05.670044     .12       0  315.02     .06       0
  386.64     .08       0  392.36     .06       0  432.41     .12       0
  663.04     .06       0  701.71     .12       0  707.02     .06       0
  844.32    .016       0  897.79     .06       0  953.53     .12       0
  1053.4    .035       0  1299.1     .12       0 1333.01    .016       0
  1366.7     .12       0 1519.33    .016       0 1549.85     .12       0
#XS Ineff= 2 , 0
          858.68 1621.24
Permanent Ineff=
       F       F
#Block Obstruct= 2 ,-1
  307.83  420.03    1650  657.76  737.35    1650
Bank Sta=1053.4,1299.1
XS Rating Curve= 0 ,0
Exp/Cntr=0.3,0.1

Type RM Length L Ch R = 1 ,45495   ,170.7,136.2,99.5
XS GIS Cut Line= 5
2099952.39625024270884.9087059112099975.92601096271049.895067543
     2100032.705      271364.4992100140.45954334 271751.43217431
2100510.21630749271968.227485613
#Sta/Elev= 30
       01625.696  20.9791626.487  44.1771629.577   87.261624.999  103.831622.647
 113.7721618.204 140.2841618.676 166.6561615.695 197.3211594.297   206.8 1588.43
   210.1 1582.44  273.76 1582.26   386.8 1582.44  388.22 1587.09 400.1661594.587
 410.1681601.675 470.1771605.987 737.6731607.965 783.151 1604.88 822.9161611.123
 841.5631610.372 885.321 1617.62 946.9011625.052 957.8041625.4581026.2611626.128
1105.1351627.4131125.1441626.5241210.6241627.1171269.6651632.2731316.6251641.435
#Mann= 15 ,-1 , 0
       0     .06       0  20.979     .08       0  44.177     .06       0
   87.26    .016       0 140.284     .06       0 197.321    .035       0
 400.166     .12       0 737.673    .016       0 841.563     .12       0
 885.321     .06       0 946.901     .12       0 957.804     .06       0
1026.261     .12       01105.135    .016       01125.144     .12       0
Bank Sta=197.321,400.166
XS Rating Curve= 0 ,0
Exp/Cntr=0.5,0.3

Type RM Length L Ch R = 1 ,45352   ,143.4,128.4,120.1
BEGIN DESCRIPTION:
Merged DS Survey GRR012BU
END DESCRIPTION:
XS GIS Cut Line= 4
2099758.94397247270999.4831258022099940.51410741271380.932989125
2100119.03264344271777.6408469812100483.69871278271992.778569895
#Sta/Elev= 30
       0 1625.65    40.7 1629.62    67.2 1624.75      77 1617.51   120.7 1615.33
   149.7 1596.45   167.7 1589.76   218.3 1582.44   263.3 1581.67   371.2 1590.64
     382 1595.78   390.4  1600.4   393.2 1603.89   404.1 1606.29   486.1 1606.15
   548.2    1609   585.4 1606.71   679.7 1608.08     702 1607.27   756.6 1604.97
   780.1 1608.08   783.6 1609.17   788.1 1610.75   811.2 1610.13   821.1 1614.03
   857.5 1616.44   919.6 1625.07  1163.4  1624.9  1224.4 1628.29  1280.9 1634.27
#Mann= 9 ,-1 , 0
       0     .08       0    67.2    .016       0   149.7    .035       0
     382     .12       0   679.7    .016       0     702     .12       0
   780.1     .06       0   783.6     .12       0   788.1     .08       0
#XS Ineff= 2 , 0
          113.64 1620.02   527.1         1611.13
Permanent Ineff=
       F       F
Bank Sta=149.7,382
XS Rating Curve= 0 ,0
Exp/Cntr(USF)=0,0
Exp/Cntr=0.5,0.3

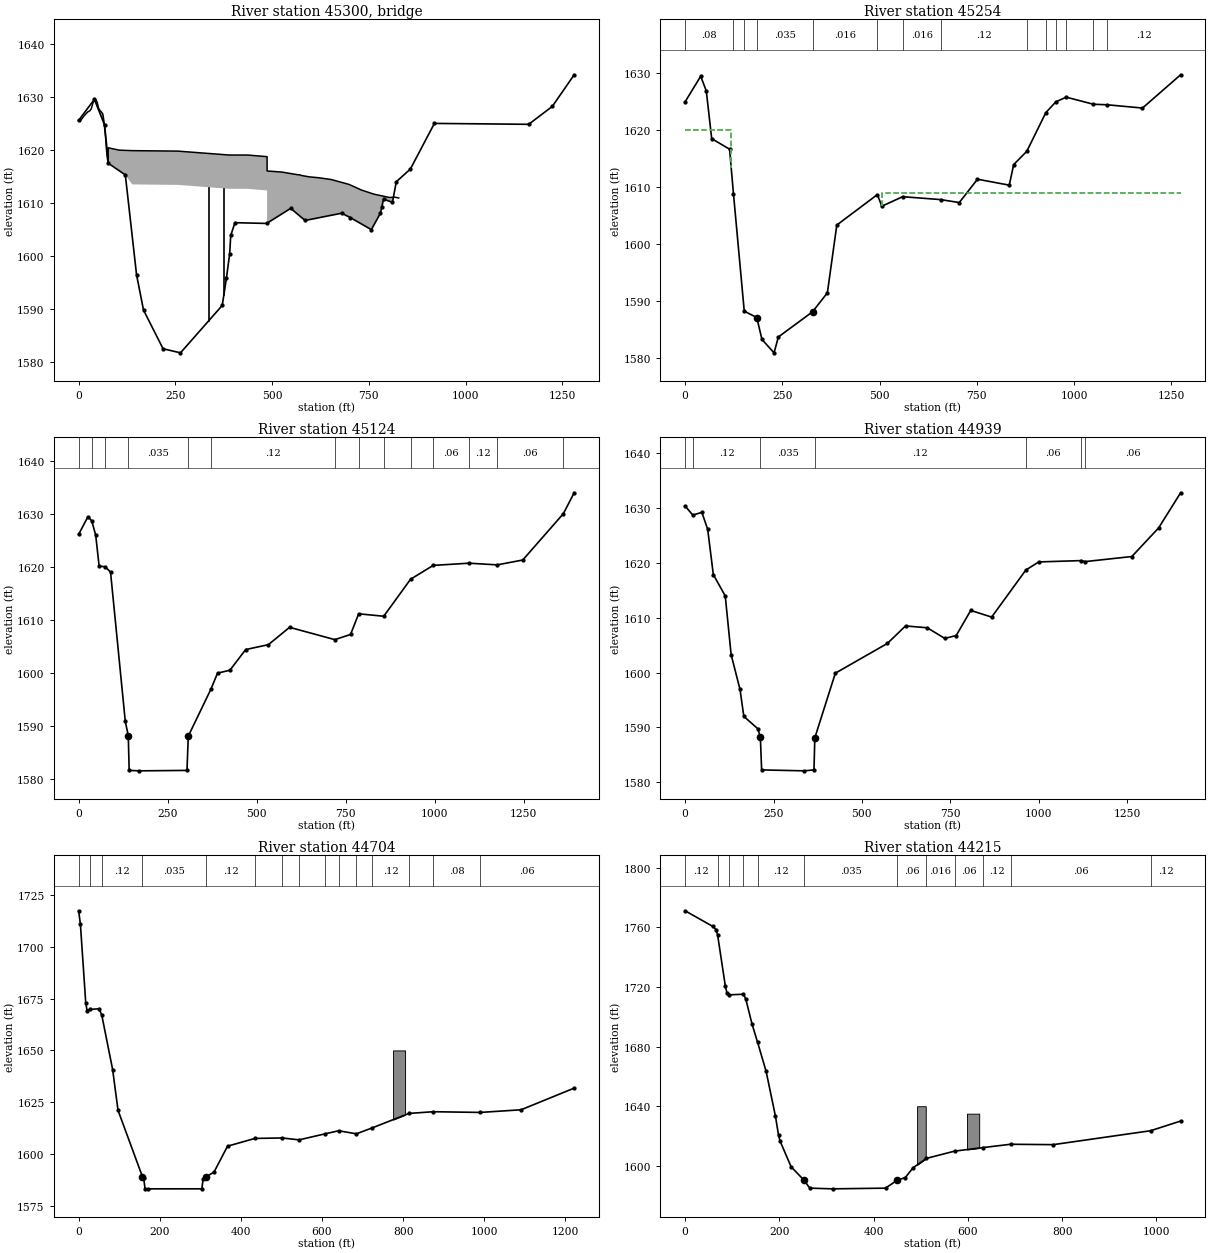
Type RM Length L Ch R = 3 ,45300   ,,,
BEGIN DESCRIPTION:
Merged US Survey GRR010RP
Fort Spring Pike Road
Picture not clear. Just two piers surveyed and is skewed in the right side of the channel
END DESCRIPTION:
Bridge Culvert--1,0,-1,-1, 0
Deck Dist Width WeirC Skew NumUp NumDn MinLoCord MaxHiCord MaxSubmerge Is_Ogee
13,25,2.6,0, 46, 46, , , 0.98, 0, 0,0,,
       0     6.7    14.2    23.8      29      31    32.7    36.4    38.3    40.1
    43.8    45.6    48.1    51.2    54.9    60.2    62.3    62.6    65.1      66
    69.8    72.3    73.5    74.8   76.23   76.33   105.2  138.65  256.57  389.24
  436.55   487.1   487.2   524.9   567.4   571.1   574.7   596.1     621   653.1
   699.4   730.6   763.3   803.3   816.7   827.4
 1625.49 1625.78 1626.51 1627.26 1627.46 1627.64 1627.84 1628.79 1629.21  1629.5
  1629.6 1629.42 1629.01 1628.02 1627.53 1627.11 1626.88 1626.79 1625.65 1625.06
 1622.26 1619.87 1618.92 1618.21  1617.7 1620.46 1620.01 1619.92 1619.83 1619.09
 1619.09 1618.78 1616.07 1615.87 1615.35 1615.36 1615.24 1614.96 1614.79 1614.45
 1613.52 1612.48 1611.69 1611.06 1611.13 1610.96
                                                                                
                                                                                
                                         1614.07 1613.62 1613.53 1613.44  1612.7
  1612.7 1612.39
                                                
       0     6.7    14.2    23.8      29      31    32.7    36.4    38.3    40.1
    43.8    45.6    48.1    51.2    54.9    60.2    62.3    62.6    65.1      66
    69.8    72.3    73.5    74.8   76.23   76.33   105.2  138.65  256.57  389.24
  436.55   487.1   487.2   524.9   567.4   571.1   574.7   596.1     621   653.1
   699.4   730.6   763.3   803.3   816.7   827.4
 1625.49 1625.78 1626.51 1627.26 1627.46 1627.64 1627.84 1628.79 1629.21  1629.5
  1629.6 1629.42 1629.01 1628.02 1627.53 1627.11 1626.88 1626.79 1625.65 1625.06
 1622.26 1619.87 1618.92 1618.21  1617.7 1620.46 1620.01 1619.92 1619.83 1619.09
 1619.09 1618.78 1616.07 1615.87 1615.35 1615.36 1615.24 1614.96 1614.79 1614.45
 1613.52 1612.48 1611.69 1611.06 1611.13 1610.96
                                                                                
                                                                                
                                         1614.07 1613.62 1613.53 1613.44  1612.7
  1612.7 1612.39
                                                
Pier Skew, UpSta & Num, DnSta & Num=  ,335, 2 ,334.3, 2 , 0 , 0 , 0 ,0,0
     2.5     2.5
    1580    1615
     2.5     2.5
    1580    1615
Pier Skew, UpSta & Num, DnSta & Num=  ,375.2, 2 ,374.4, 2 , 0 , 0 , 0 ,0,0
     2.5     2.5
  1591.4  1613.1
     2.5     2.5
    1593  1613.1
BR Coef=-1 , 1 , 0 ,, 0 ,,,0.8,0,2,0,
WSPro=,,,, 1 ,,,, 0 ,,,, 0 ,,,,-1 ,-1 ,-1 , 0 , 0 , 0 , 0 , 0
BC Design=,, 0 ,, 0 ,,0,,,,
BC HTab HWMax=0
BC HTab TWMax=0
BC HTab MaxFlow=0
BC Use User HTab Curves=0
BC User HTab FreeFlow(D)= 0

Type RM Length L Ch R = 1 ,45254   ,108.2,106.5,118.8
BEGIN DESCRIPTION:
Merged US Survey GRR008BD
END DESCRIPTION:
XS GIS Cut Line= 4
 2099633.8284173271074.2472990132099858.12093693271474.006755776
2100009.17508281271742.5474595552100451.65692426271991.252770442
#Sta/Elev= 30
       0 1624.94    40.1 1629.42    54.5 1626.85    68.4 1618.49   114.4 1616.64
   124.4  1608.8   152.1 1588.26   184.3 1587.15   197.6 1583.31   228.7 1580.96
   239.8 1583.74   327.6 1588.15 365.7871591.465 390.0341603.345   494.4 1608.69
   505.7 1606.64   559.3 1608.32   656.9 1607.81   704.9 1607.29   751.8 1611.38
   833.5 1610.34   844.8 1613.94   878.6 1616.28   927.6 1623.06   953.3 1624.94
   979.8 1625.76  1049.6 1624.52  1085.8 1624.42    1176 1623.85  1274.1 1629.68
#Mann= 14 ,-1 , 0
       0     .08       0   124.4    .016       0   152.1     .08       0
   184.3    .035       0   327.6    .016       0   494.4     .12       0
   559.3    .016       0   656.9     .12       0   878.6    .016       0
   927.6     .12       0   953.3     .06       0   979.8     .12       0
  1049.6     .08       0  1085.8     .12       0
#XS Ineff= 2 , 0
          118.65 1620.01   507.2            1609
Permanent Ineff=
       F       F
Bank Sta=184.3,327.6
XS Rating Curve= 0 ,0
Exp/Cntr(USF)=0,0
Exp/Cntr=0.5,0.3

Type RM Length L Ch R = 1 ,45124   ,256.9,184.6,86.8
XS GIS Cut Line= 4
     2099544.142      271132.764     2099766.053      271526.476
2100105.33476189271903.8329753622100499.88576078272079.466141008
#Sta/Elev= 30
       01626.101  26.2441629.449  36.8471628.661  47.9211625.949  57.5551620.109
  74.5081619.998  89.5731618.984     1311590.787   139.4 1588.12   141.9 1581.55
  170.51 1581.47   304.2 1581.55   307.9 1588.02 372.0291596.969 389.9341599.911
 424.7541600.463  468.991604.362 532.7821605.284 592.1571608.559  719.251606.238
 763.414 1607.21 786.2821611.113 856.648 1610.65 931.8761617.634 995.528 1620.25
1096.0821620.6651175.0891620.3481246.9131621.265 1360.851630.0061391.2761633.956
#Mann= 14 ,-1 , 0
       0     .08       0  36.847    .016       0  74.508     .12       0
   139.4    .035       0   307.9     .06       0 372.029     .12       0
  719.25    .016       0 786.282     .12       0 856.648    .016       0
 931.876     .12       0 995.528     .06       01096.082     .12       0
1175.089     .06       0 1360.85     .12       0
Bank Sta=139.4,307.9
XS Rating Curve= 0 ,0
Exp/Cntr=0.3,0.1

Type RM Length L Ch R = 1 ,44939   ,302.6,235.3,140.7
XS GIS Cut Line= 5
     2099304.336      271379.729     2099744.577      271576.585
2099972.67315024271766.7858558952100088.88910755271900.543844495
2100493.55098667272084.937133168
#Sta/Elev= 30
       01630.369  21.641 1628.72  47.459  1629.2  63.8591626.119  79.8041617.872
 113.5281613.965 130.1181603.271 155.2761596.922 166.057 1592.01  205.591589.759
   212.8 1588.22   216.4 1582.25  336.69 1582.08   364.4 1582.25   366.8  1588.1
 424.8181599.887 571.9361605.309  623.24  1608.5  684.641608.167 734.3691606.219
 766.6071606.756 807.6381611.329  866.761610.112 963.4621618.694 999.9631620.173
 1118.94 1620.411131.8831620.2361263.1561621.1561338.8691626.3711401.1281632.779
#Mann= 7 ,-1 , 0
       0    .016       0  21.641     .12       0   212.8    .035       0
   366.8     .12       0 963.462     .06       0 1118.94     .12       0
1131.883     .06       0
Bank Sta=212.8,366.8
XS Rating Curve= 0 ,0
Exp/Cntr=0.3,0.1

Type RM Length L Ch R = 1 ,44704   ,489.8,488.9,492.1
XS GIS Cut Line= 6
      2099382.67      271770.285     2099430.616      271766.408
     2099761.802      271707.7682099966.09488851271775.556871541
2100085.59997668271906.0257292742100490.43442598272090.569125963
#Sta/Elev= 30
       01717.451   4.3751710.981  17.5411672.937  20.8321669.223  27.4161669.777
  50.4851670.133  57.1491666.962  83.8041640.771  97.1311621.047   157.1 1589.09
   160.4 1588.18   163.8 1583.14  171.97 1583.13   303.7 1583.14     307 1588.02
   314.4    1589 333.6941591.203 367.0121603.731 434.5121607.482 501.1721607.707
 543.5231606.797 606.9761609.674 640.9771611.188 684.6931609.704 723.5981612.564
 814.1821619.561 874.2391620.383 990.0251620.0421090.5771621.3191221.5271631.779
#Mann= 15 ,-1 , 0
       0     .12       0  27.416    .016       0  57.149     .12       0
   157.1    .035       0   314.4     .12       0 434.512    .016       0
 501.172     .12       0 543.523    .016       0 606.976     .12       0
 640.977     .06       0 684.693    .016       0 723.598     .12       0
 814.182     .06       0 874.239     .08       0 990.025     .06       0
#Block Obstruct= 1 ,-1
  775.11  804.71    1650
Bank Sta=157.1,314.4
XS Rating Curve= 0 ,0
Exp/Cntr=0.3,0.1

Type RM Length L Ch R = 1 ,44215   ,397.8,399.1,411.9
XS GIS Cut Line= 3
2099443.50493709272250.2475573932100008.92877601 272165.54158251
  2100486.131831272116.564622237
#Sta/Elev= 30
       0  1771.2      59 1760.66    65.6 1758.55   68.861755.213    85.5 1720.41
    88.9 1715.89   93.991714.789  123.861715.177   128.7 1711.99   141.9 1695.31
  153.731682.975   171.8 1663.52   191.7  1633.3   198.3 1620.42   201.7 1616.45
   224.9 1599.37  251.82 1590.49   264.7    1585  312.96 1584.54   425.2    1585
   450.5 1590.44   467.1 1592.07   483.6 1598.64  512.131605.005  571.87 1609.85
  631.25 1612.21  690.641614.458     781  1614.2  987.561623.544  1051.4 1630.05
#Mann= 12 ,-1 , 0
       0     .12       0   68.86     .06       0   93.99    .016       0
  123.86     .06       0  153.73     .12       0  251.82    .035       0
   450.5     .06       0  512.13    .016       0  571.87     .06       0
  631.25     .12       0  690.64     .06       0  987.56     .12       0
#Block Obstruct= 2 ,-1
  492.22   510.6    1640  598.11     624    1635
Bank Sta=251.82,450.5
XS Rating Curve= 0 ,0
Exp/Cntr=0.3,0.1