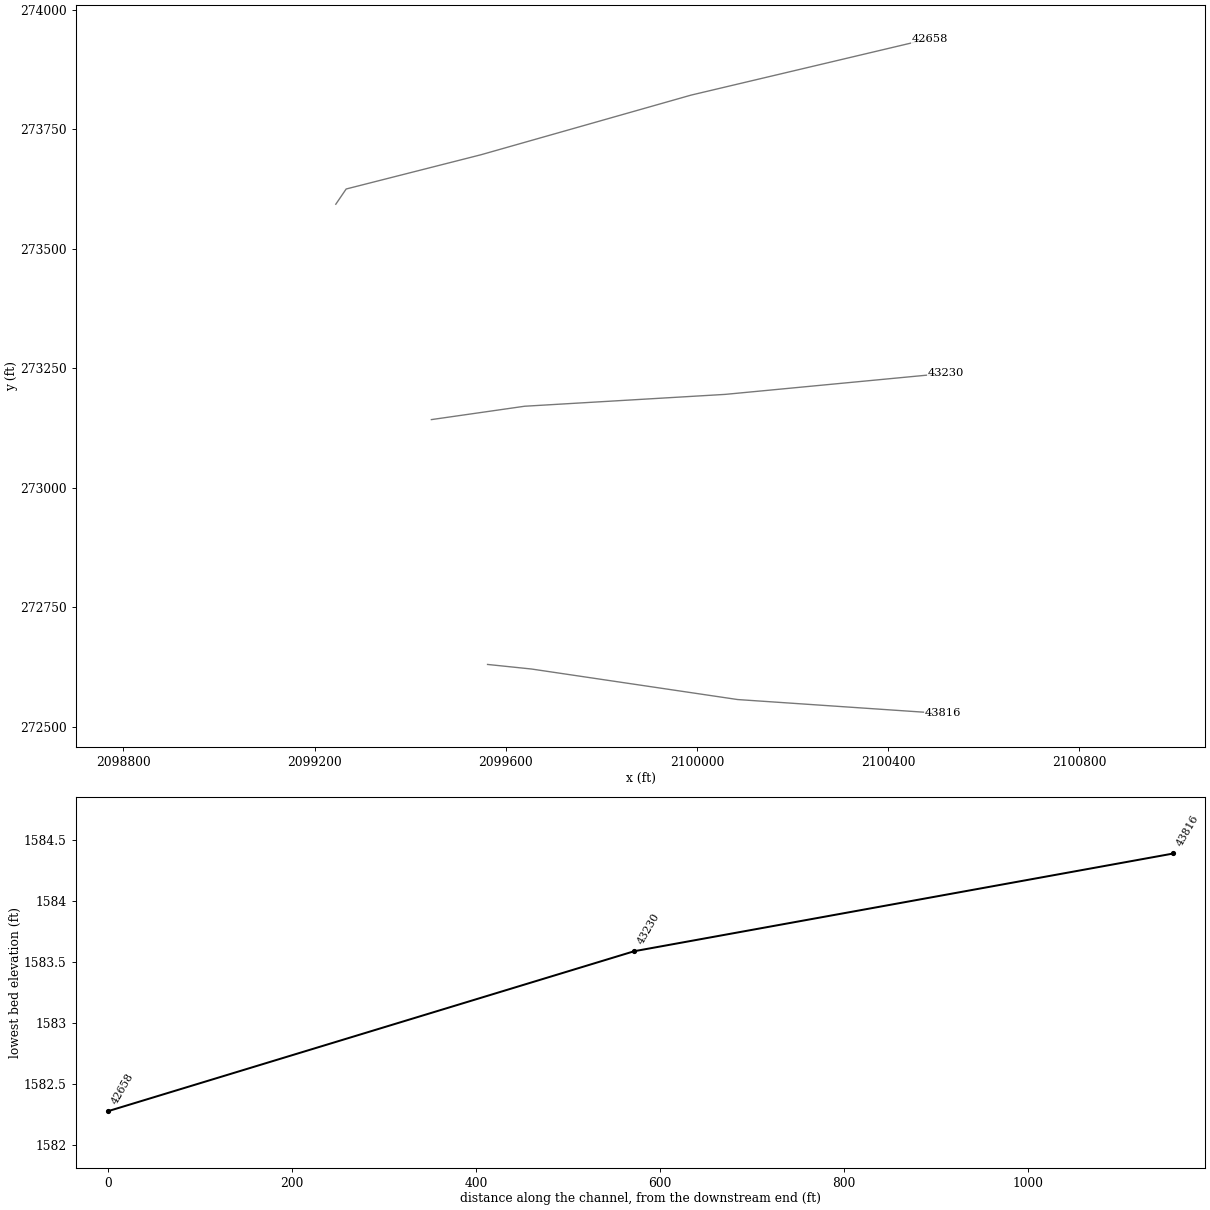
HEC-RAS study GRBRRV3.prj: GRBRRV3

--- GRBRRV3.g01 (geometry) --- (continued)

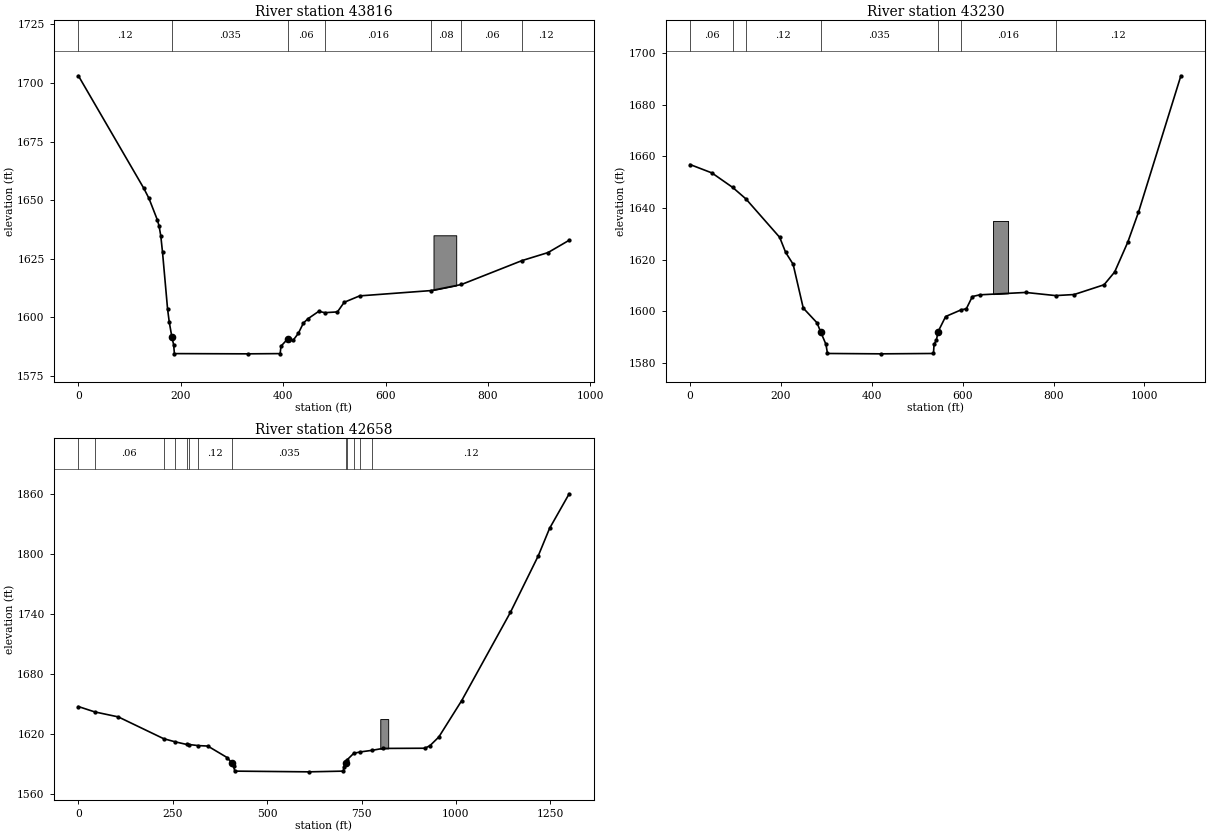
Type RM Length L Ch R = 1 ,43816   ,569.7,586,638.5
XS GIS Cut Line= 4
     2099561.976      272630.275     2099654.009      272620.702
     2100085.155      272556.8712100514.29576022272527.728079783
#Sta/Elev= 30
       0 1703.09   127.8 1655.03   137.7 1650.81   154.3 1641.51   157.6 1638.92
   160.9 1634.77   164.3 1627.76   174.2 1603.45   177.5  1597.9   182.71591.413
     186 1588.31   187.5 1584.49  330.31 1584.39     394 1584.49   395.7 1587.66
   408.5 1590.71   419.6 1590.22   429.6 1593.16   439.5 1597.56   448.9 1599.46
   469.4 1602.53  481.291601.962   505.9 1602.29   519.1 1606.39   549.3 1609.13
  688.931611.396  748.141613.994  866.57 1624.21   917.1 1627.61   958.5 1632.88
#Mann= 7 ,-1 , 0
       0     .12       0   182.7    .035       0   408.5     .06       0
  481.29    .016       0  688.93     .08       0  748.14     .06       0
  866.57     .12       0
#Block Obstruct= 1 ,-1
  693.52  737.87    1635
Bank Sta=182.7,408.5
XS Rating Curve= 0 ,0
Exp/Cntr=0.3,0.1

Type RM Length L Ch R = 1 ,43230   ,548,572.1,629.4
XS GIS Cut Line= 4
     2099444.455      273142.403     2099639.533      273170.351
     2100059.062      273195.1412100519.93689514273239.054233082
#Sta/Elev= 30
       0 1656.82      48 1653.58   93.81 1647.96  122.741643.553   197.2 1628.66
   210.3 1622.86   226.8 1618.24   249.1 1601.29   279.4 1595.59  287.64 1591.99
   299.1 1587.24   302.4 1583.73  420.49 1583.59   535.7 1583.73     537 1587.25
   542.3 1588.97   545.6 1592.07   562.5 1598.03  596.78 1600.62     608 1601.01
   621.3 1605.75   637.6 1606.42   738.7 1607.34  804.421606.127   845.3 1606.53
   911.2 1610.31   934.5 1615.24   963.4 1626.78     987 1638.39  1080.3 1691.16
#Mann= 7 ,-1 , 0
       0     .06       0   93.81     .08       0  122.74     .12       0
  287.64    .035       0   545.6     .12       0  596.78    .016       0
  804.42     .12       0
#Block Obstruct= 1 ,-1
  666.87  699.92    1635
Bank Sta=287.64,545.6
XS Rating Curve= 0 ,0
Exp/Cntr=0.3,0.1

Type RM Length L Ch R = 1 ,42658   ,472.2,554.1,663.9
XS GIS Cut Line= 5
     2099244.443      273592.916      2099266.14      273624.743
     2099548.132      273696.353     2099987.871      273821.133
2100487.51865579273939.323797408
#Sta/Elev= 30
       0  1647.5   43.081642.174   105.7 1637.16  225.921615.386   256.41612.249
  286.871609.636     2931609.586  317.351608.501   342.7 1608.04   394.4 1596.45
   406.4 1591.03     411  1587.8   414.4 1582.99  609.99 1582.28   702.2 1582.99
   703.2 1587.38     708 1590.65   711.1 1594.03  729.471600.811   747.11602.186
   777.81603.758   806.3 1605.66   917.6 1605.86   931.1 1608.38   954.7 1617.08
  1015.4 1653.52  1144.4 1741.65    1218 1797.98    1248 1825.44    1300 1860.05
#Mann= 13 ,-1 , 0
       0     .08       0   43.08     .06       0  225.92     .12       0
   256.4     .08       0  286.87     .12       0     293     .08       0
  317.35     .12       0   406.4    .035       0     708     .12       0
   711.1     .06       0  729.47     .12       0   747.1    .016       0
   777.8     .12       0
#Block Obstruct= 1 ,-1
  799.63  820.62    1635
Bank Sta=406.4,708
XS Rating Curve= 0 ,0
Exp/Cntr=0.3,0.1