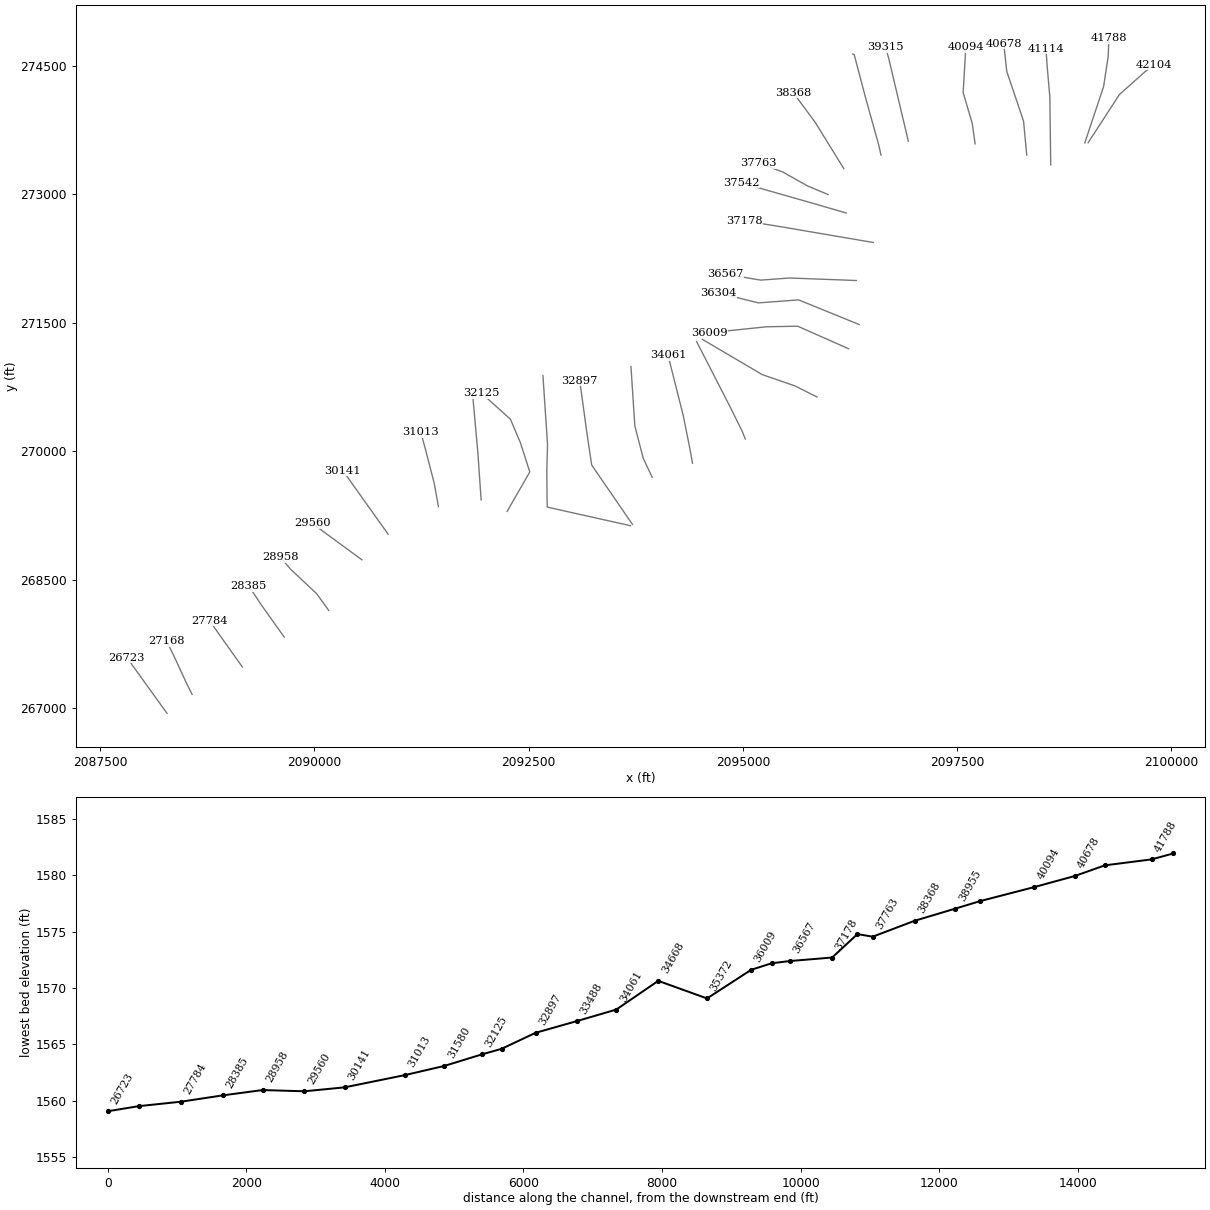
HEC-RAS study GRBRRV3.prj: GRBRRV3

--- GRBRRV3.g01 (geometry) --- (continued)

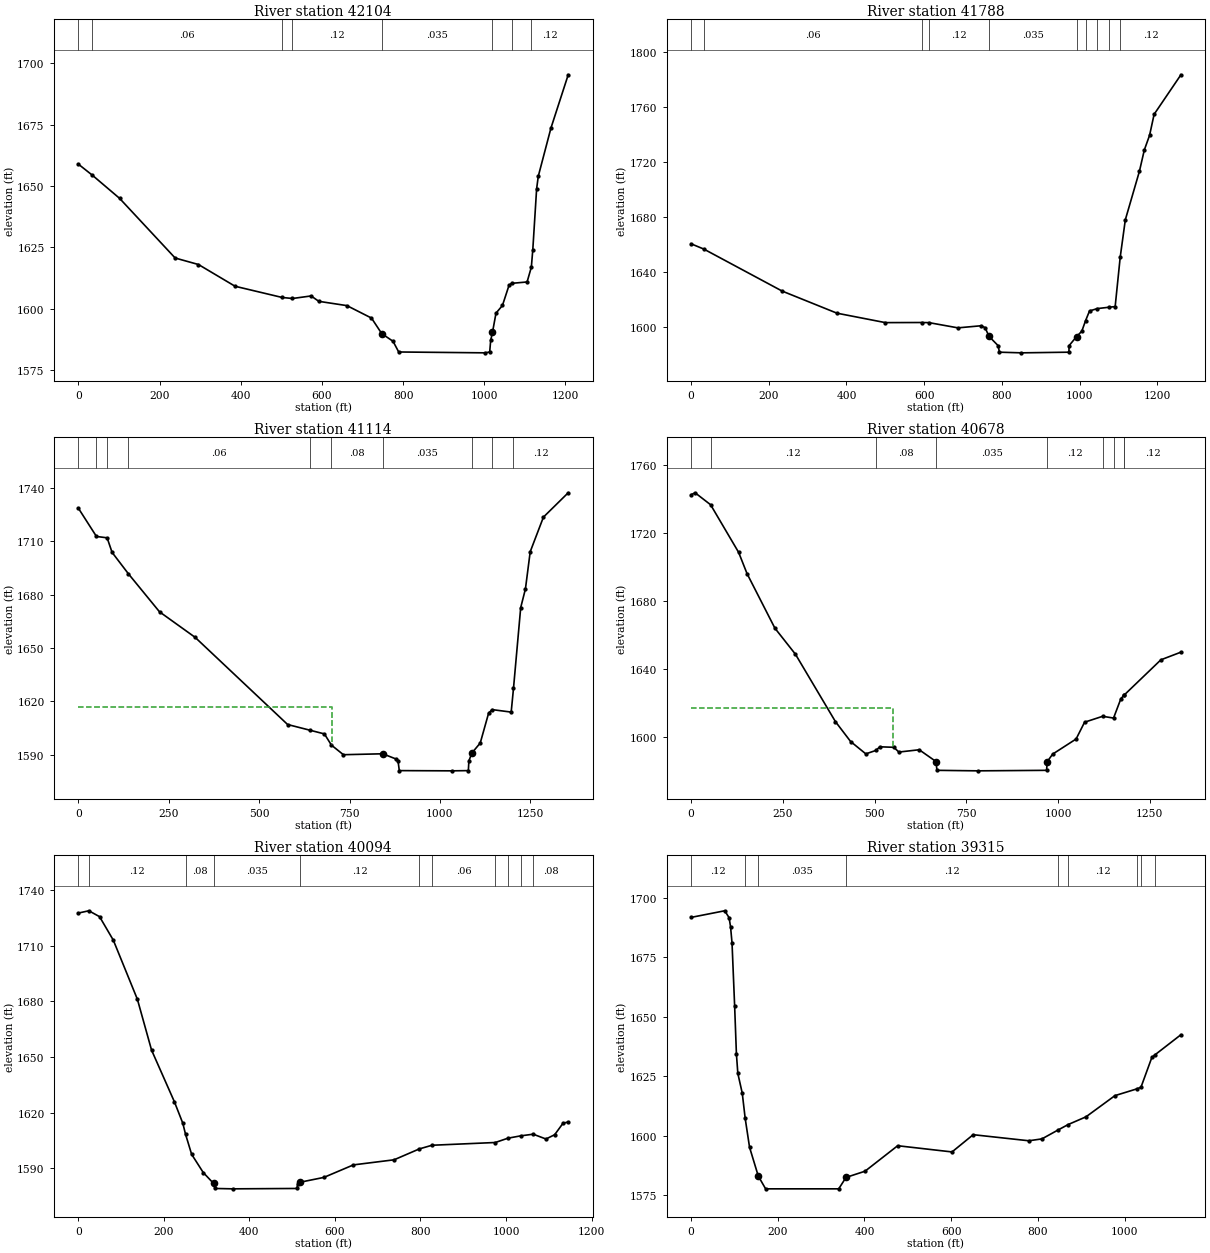
Type RM Length L Ch R = 1 ,42104   ,176.5,315.5,445.8
XS GIS Cut Line= 4
2099026.79114654273599.353237828     2099392.532      274162.878
     2099698.197       274434.85     2099800.192       274508.51
#Sta/Elev= 30
       0 1658.91   34.49 1654.39   101.6 1644.95   238.5 1620.61   295.9 1617.96
   386.1 1609.09  501.981604.522  527.491604.098   573.4 1605.14   592.4 1602.94
   661.7 1601.19   722.2 1596.11   747.4 1589.78   775.3 1586.63   789.2 1582.28
  1002.2 1581.93  1013.4 1582.28  1015.8 1587.05  1020.2 1590.23  1028.9 1598.12
  1044.8 1601.25  1061.1 1609.53 1067.371610.281  1105.5 1610.84 1115.991616.879
  1119.6 1624.07    1129 1648.86  1133.1 1653.98  1164.3 1673.64  1206.8 1695.36
#Mann= 8 ,-1 , 0
       0     .08       0   34.49     .06       0  501.98     .08       0
  527.49     .12       0   747.4    .035       0  1020.2     .12       0
 1067.37    .016       0 1115.99     .12       0
Bank Sta=747.4,1020.2
XS Rating Curve= 0 ,0
Exp/Cntr=0.3,0.1

Type RM Length L Ch R = 1 ,41788   ,597.6,674.7,713.1
XS GIS Cut Line= 4
2098987.96788048273597.159262252     2099208.044      274256.445
      2099261.23      274606.691     2099269.894      274818.288
#Sta/Elev= 30
       0 1660.54   32.811656.717   234.5 1626.22   375.7 1610.17   500.3 1603.33
  593.331603.415  612.541603.321     687 1599.53   747.1 1601.07     757 1599.65
     767 1593.37   790.8 1586.53   793.7 1581.87  850.64  1581.4   972.7 1581.87
   973.3 1586.66   992.5 1593.21  1005.9 1597.09 1015.721604.825  1025.8 1611.79
  1045.61613.505  1075.21614.473  1091.8 1614.98 1104.761650.757    1118    1678
  1154.2 1713.11  1166.9 1728.66  1180.4 1739.27  1192.1 1754.53  1261.1 1783.21
#Mann= 10 ,-1 , 0
       0     .08       0   32.81     .06       0  593.33     .08       0
  612.54     .12       0     767    .035       0   992.5     .12       0
 1015.72     .08       0  1045.6    .016       0  1075.2     .08       0
 1104.76     .12       0
Bank Sta=767,992.5
XS Rating Curve= 0 ,0
Exp/Cntr=0.3,0.1

Type RM Length L Ch R = 1 ,41114   ,360,435.7,474.3
XS GIS Cut Line= 4
2098590.78891131273341.914264849     2098580.487      274135.923
     2098549.318      274491.312     2098535.543      274694.932
#Sta/Elev= 30
       0 1728.58   50.051712.673   79.591711.902    93.3 1703.71  138.671691.618
   224.5 1670.29     323 1655.94   578.8 1606.92  640.85  1603.7   680.6 1601.63
  699.93 1595.34   733.1 1589.94   841.9 1590.46   877.6 1587.62   884.4 1586.17
   887.7    1581 1034.15 1580.87  1078.7    1581  1080.2 1586.47  1088.6 1590.93
  1111.6 1596.51  1134.7 1613.27 1144.341615.303  1197.2  1613.9 1203.561627.233
  1223.5 1672.65  1236.6 1683.18  1249.8 1704.07  1286.4 1723.55  1354.9 1737.23
#Mann= 10 ,-1 , 0
       0     .12       0   50.05    .016       0   79.59     .12       0
  138.67     .06       0  640.85     .12       0  699.93     .08       0
   841.9    .035       0  1088.6     .12       0 1144.34    .016       0
 1203.56     .12       0
#XS Ineff= 2 , 0
          701.28 1617.03
Permanent Ineff=
       F       F
Bank Sta=841.9,1088.6
XS Rating Curve= 0 ,0
Exp/Cntr=0.3,0.1

Type RM Length L Ch R = 1 ,40678   ,580,584.2,507.2
XS GIS Cut Line= 4
2098310.77186246273457.0974884772098274.00910411273851.188913908
     2098077.779      274433.3682098042.64811311274755.940287894
#Sta/Elev= 30
       0 1742.47      11 1743.62   53.231736.571   129.6 1708.54   152.6 1695.97
   228.4  1663.9   284.4 1648.56   393.2 1608.94   434.7 1597.18   476.1 1589.91
   503.41591.917   514.2 1594.07   552.3 1593.78   566.2 1590.98   621.6 1592.33
   667.6 1585.36   669.8 1580.22  780.68 1579.92   968.5 1580.22   970.5 1585.37
   985.1 1589.76    1049 1598.66  1072.1 1608.55 1121.341612.027 1151.051610.988
  1171.1 1622.42 1179.181624.329 1180.771624.697    1280 1645.28  1334.6 1649.79
#Mann= 9 ,-1 , 0
       0     .08       0   53.23     .12       0   503.4     .08       0
   667.6    .035       0   970.5     .12       0 1121.34    .016       0
 1151.05     .12       0 1179.18     .08       0 1180.77     .12       0
#XS Ineff= 2 , 0
          549.72 1617.14
Permanent Ineff=
       F       F
Bank Sta=667.6,970.5
XS Rating Curve= 0 ,0
Exp/Cntr=0.3,0.1

Type RM Length L Ch R = 1 ,40094   ,772.6,778.6,802.1
XS GIS Cut Line= 4
2097708.48844344273587.177082278     2097675.385      273823.588
     2097569.022      274185.9032097600.24754755274714.182019231
#Sta/Elev= 30
       0 1727.49    24.61728.724    49.6 1725.55    81.8 1712.88   138.1 1681.02
   171.2 1653.67   224.6 1625.84   244.3 1614.26  250.591608.406   264.9 1597.54
   292.1 1587.71   316.1 1581.88   319.5 1579.14  361.01 1578.94     511 1579.14
   513.4 1581.79   517.8 1582.47   574.2  1585.1   643.2 1591.84   738.3 1594.58
  797.38 1600.45  826.971602.417  974.92  1603.9 1004.511606.213 1034.091607.476
 1063.681608.377  1093.5 1605.78  1113.8 1608.09  1133.5 1614.31  1145.5 1614.93
#Mann= 11 ,-1 , 0
       0     .08       0    24.6     .12       0  250.59     .08       0
   316.1    .035       0   517.8     .12       0  797.38     .08       0
  826.97     .06       0  974.92    .016       0 1004.51     .08       0
 1034.09    .016       0 1063.68     .08       0
Bank Sta=316.1,517.8
XS Rating Curve= 0 ,0
Exp/Cntr=0.3,0.1

Type RM Length L Ch R = 1 ,39315   ,353,359.8,367.5
XS GIS Cut Line= 3
2096929.16883471273618.8838700282096700.12427567274585.586641269
2096663.07294994274716.950432482
#Sta/Elev= 30
       0 1691.65    77.6 1694.43    87.7 1691.55    91.1 1687.72    94.5 1680.91
   100.5 1654.52   104.6 1634.39   107.9 1626.15   118.1 1617.85   124.8 1607.34
   134.9 1595.16   155.1 1583.04     172  1577.7   340.6  1577.7   357.4 1582.49
   401.3  1585.1   476.6  1595.8     602 1593.19   650.8 1600.43   779.2 1597.88
   809.4 1598.67   846.3 1602.38   869.9 1604.69     911 1607.93   977.8 1616.83
  1028.3 1619.66  1037.8 1620.33  1062.9 1632.85    1071 1634.08    1130  1642.4
#Mann= 9 ,-1 , 0
       0     .12       0   124.8     .08       0   155.1    .035       0
   357.4     .12       0   846.3    .016       0   869.9     .12       0
  1028.3     .08       0  1037.8    .016       0    1071     .08       0
Bank Sta=155.1,357.4
XS Rating Curve= 0 ,0
Exp/Cntr(USF)=0,0
Exp/Cntr=0.3,0.1

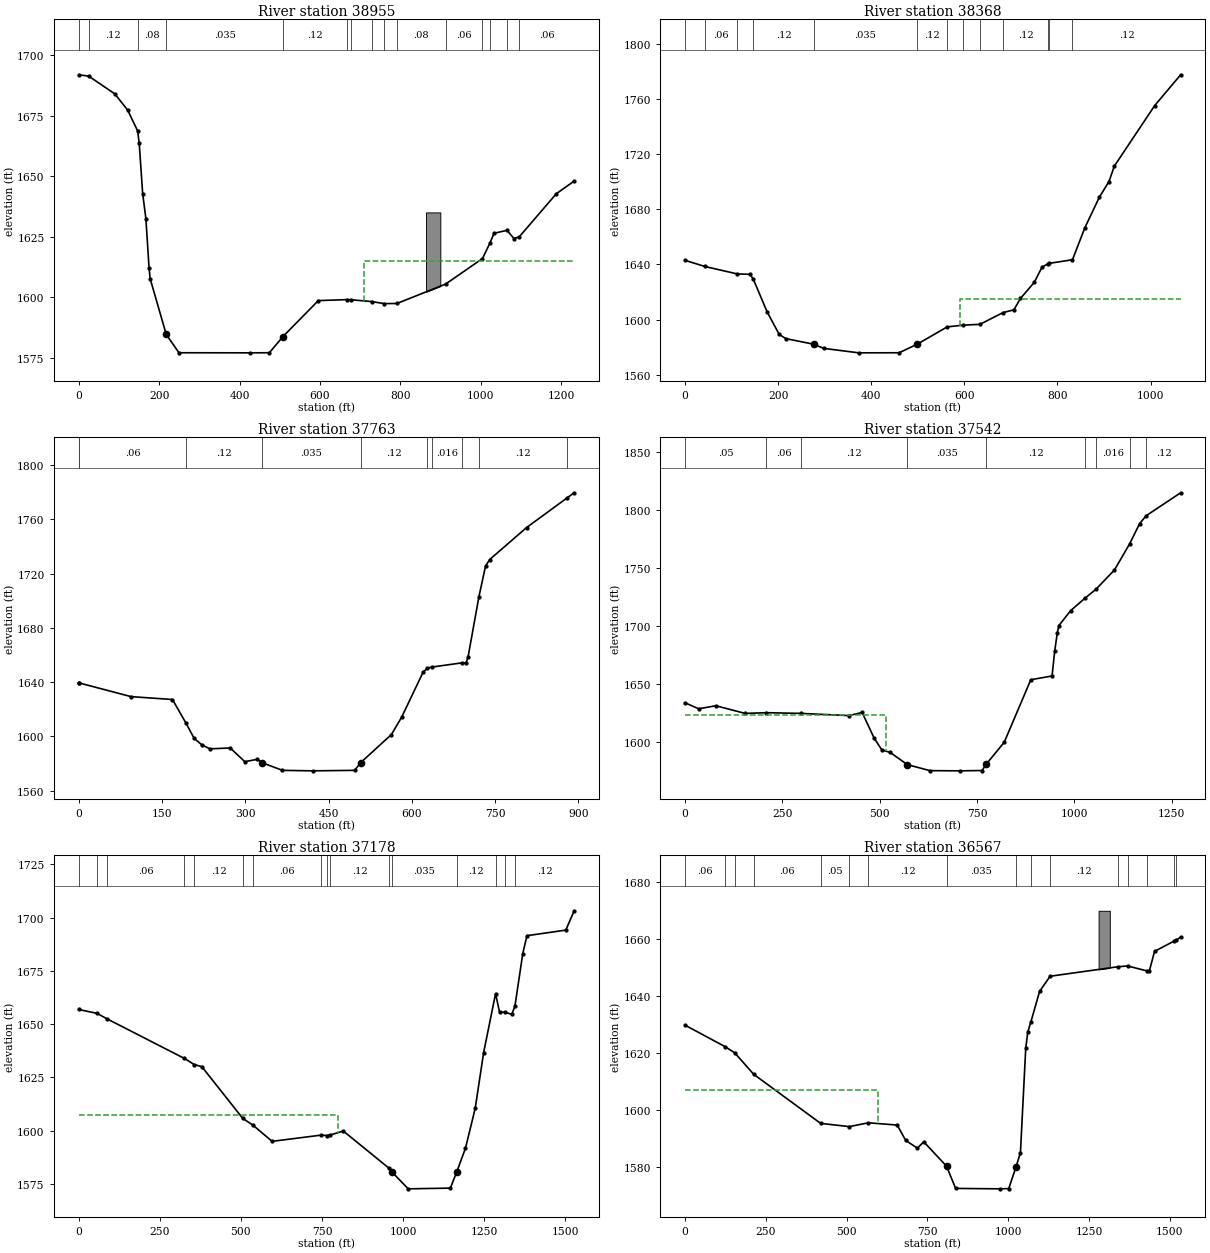
Type RM Length L Ch R = 1 ,38955   ,542.7,587.4,650.3
XS GIS Cut Line= 5
     2096610.207      273455.822      2096583.79      273574.755
2096433.24074222274114.8183078712096297.27982449274629.029471049
2096280.78123523274635.165132344
#Sta/Elev= 30
       0 1691.81   25.261691.235    89.8 1683.94   121.8 1677.27  146.621668.661
   150.7 1663.45   159.2 1642.76   167.2 1632.46   175.2 1611.86   177.9 1607.61
   217.8 1584.61   249.4 1577.07  425.71 1577.03   474.2 1577.07   508.1 1583.77
     596  1598.6  667.89    1599  676.141598.961  729.051598.187   759.61597.348
  791.391597.403  912.361605.416 1004.021615.948 1022.531622.322  1032.8 1626.39
 1065.12  1627.6  1082.4 1624.19 1095.671624.952  1187.6 1642.71    1232 1647.94
#Mann= 15 ,-1 , 0
       0      .1       0   25.26     .12       0  146.62     .08       0
   217.8    .035       0   508.1     .12       0  667.89     .08       0
  676.14     .12       0  729.05     .06       0   759.6    .016       0
  791.39     .08       0  912.36     .06       0 1004.02     .12       0
 1022.53    .016       0 1065.12     .08       0 1095.67     .06       0
#XS Ineff= 2 , 0
                          708.31         1614.85
Permanent Ineff=
       F       F
#Block Obstruct= 1 ,-1
  863.51  899.23    1635
Bank Sta=217.8,508.1
XS Rating Curve= 0 ,0
Exp/Cntr=0.3,0.1

Type RM Length L Ch R = 1 ,38368   ,529.6,604.7,686
XS GIS Cut Line= 4
     2096177.228       273296.75     2095996.677      273588.691
2095844.07676542273835.9241176722095587.91221981274182.456642649
#Sta/Elev= 30
       0 1642.98   42.361638.539  111.811633.151   139.6 1632.82  146.54 1629.35
     176  1605.8   202.2 1589.28   216.5 1586.24   276.1 1582.22   297.8 1579.19
  373.13 1575.95   459.7    1576   498.3 1582.12  563.171594.766  597.881596.002
  633.541596.614  683.271605.137   706.4 1607.11   720.5 1615.34   750.3 1627.07
   766.8    1638  779.441640.456  782.651640.805  832.341643.425   858.9 1666.61
   890.3  1688.9   910.7 1700.05   922.3  1711.3    1009 1755.14  1064.7 1777.44
#Mann= 13 ,-1 , 0
       0     .05       0   42.36     .06       0  111.81     .08       0
  146.54     .12       0   276.1    .035       0   498.3     .12       0
  563.17     .08       0  597.88     .12       0  633.54     .08       0
  683.27     .12       0  779.44     .08       0  782.65    .016       0
  832.34     .12       0
#XS Ineff= 2 , 0
                          590.29         1614.86
Permanent Ineff=
       F       F
Bank Sta=276.1,498.3
XS Rating Curve= 0 ,0
Exp/Cntr=0.3,0.1

Type RM Length L Ch R = 1 ,37763   ,178.6,220.7,240.1
XS GIS Cut Line= 4
     2095993.197      272995.503     2095755.678      273094.492
     2095466.097      273257.5562095182.27588265273362.927039118
#Sta/Elev= 30
       0 1639.51    1.371639.332    94.4 1629.28     169 1627.16  193.371609.723
   208.1 1598.42   222.4 1593.53   236.6 1590.79     273 1591.39   299.3  1581.3
   321.9 1583.05   329.9  1580.6   367.1  1574.9  421.37 1574.54     497  1574.9
   507.9 1580.58   563.3 1601.34   581.7 1614.11   620.4 1647.34   627.41650.085
  635.941651.083  690.421654.206   697.8 1654.23   701.3 1658.52  720.791702.821
   732.8 1725.63   740.3 1730.43   806.7    1754  879.46 1775.82   892.4 1779.65
#Mann= 10 ,-1 , 0
       0     .05       0    1.37     .06       0  193.37     .12       0
   329.9    .035       0   507.9     .12       0   627.4     .08       0
  635.94    .016       0  690.42     .08       0  720.79     .12       0
  879.46    .016       0
Bank Sta=329.9,507.9
XS Rating Curve= 0 ,0
Exp/Cntr=0.3,0.1

Type RM Length L Ch R = 1 ,37542   ,348,364.5,376.6
XS GIS Cut Line= 3
2096205.19913526272779.8038978832095798.55985828272898.242522245
2094981.33335018273131.171816824
#Sta/Elev= 30
       0 1633.45    34.8 1628.29    79.2  1630.9   154.4 1624.29     209 1624.91
   297.9  1624.3   420.9  1622.4   454.9 1625.11   485.7 1603.01   505.6 1592.78
   526.7 1590.69     571 1580.15     629 1574.94  706.95 1574.77   763.1 1575.05
   773.7 1580.47   820.1 1599.48   888.3 1653.34   942.9 1656.59   949.7 1678.07
   956.5 1694.05   960.6  1700.1   990.6  1712.9  1028.2 1723.85  1055.5 1731.29
  1103.2 1747.96    1142 1770.38    1168 1787.99  1184.9 1794.82  1273.3 1814.56
#Mann= 9 ,-1 , 0
       0     .05       0     209     .06       0   297.9     .12       0
     571    .035       0   773.7     .12       0  1028.2     .08       0
  1055.5    .016       0    1142     .08       0  1184.9     .12       0
#XS Ineff= 2 , 0
           516.5 1622.68
Permanent Ineff=
       F       F
Bank Sta=571,773.7
XS Rating Curve= 0 ,0
Exp/Cntr(USF)=0,0
Exp/Cntr=0.3,0.1

Type RM Length L Ch R = 1 ,37178   ,565.6,611.3,636.2
BEGIN DESCRIPTION:
Not Burnt
END DESCRIPTION:
XS GIS Cut Line= 3
2096520.10615957272436.090470208     2095463.539      272616.317
     2095014.413      272689.192
#Sta/Elev= 30
       0 1656.86   56.351655.049   86.311652.559  326.031633.863  355.991631.031
   379.7    1630  505.811605.713  535.781602.734   596.2 1594.97  745.531597.864
  765.341597.712  775.491598.017   815.9 1599.77  955.281582.492   965.8 1580.51
  1015.6 1572.69  1145.4 1573.03  1165.3 1580.76  1191.9 1591.76  1221.8 1610.41
  1247.9 1636.66  1284.61664.294  1296.9 1655.62 1314.521655.544  1334.8 1654.54
 1344.441658.596  1368.4 1683.05  1381.3 1691.48    1501  1694.1  1526.8 1703.17
#Mann= 16 ,-1 , 0
       0     .06       0   56.35     .05       0   86.31     .06       0
  326.03    .016       0  355.99     .12       0  505.81     .08       0
  535.78     .06       0  745.53     .12       0  765.34     .06       0
  775.49     .12       0  955.28     .08       0   965.8    .035       0
  1165.3     .12       0  1284.6    .016       0 1314.52     .08       0
 1344.44     .12       0
#XS Ineff= 2 , 0
          799.14 1607.56
Permanent Ineff=
       F       F
Bank Sta=965.8,1165.3
XS Rating Curve= 0 ,0
Exp/Cntr=0.3,0.1

Type RM Length L Ch R = 1 ,36567   ,256.5,262.8,267.8
BEGIN DESCRIPTION:
Not Burnt
END DESCRIPTION:
XS GIS Cut Line= 4
2096322.59026281271992.476113637     2095542.104      272021.714
     2095205.419      271997.0592094796.25052247272066.135776086
#Sta/Elev= 30
       0 1629.83  123.931622.286  153.491620.139  212.611612.567  419.511595.358
  508.191594.231   567.31595.565   656.5 1594.77   682.7 1589.37   718.9 1586.67
   738.6 1588.89   809.1 1580.34   837.2 1572.53  974.19 1572.38  1001.6 1572.47
  1023.9    1580  1037.8 1585.09  1054.3  1621.9  1060.9 1627.58 1070.361631.074
    1097 1641.68 1129.721647.021 1339.411650.348 1369.361650.624 1429.271648.893
  1436.8 1648.88  1452.8 1655.75 1512.351659.305 1519.141659.611  1533.6 1660.76
#Mann= 16 ,-1 , 0
       0     .06       0  123.93    .016       0  153.49     .12       0
  212.61     .06       0  419.51     .05       0  508.19     .06       0
   567.3     .12       0   809.1    .035       0  1023.9     .12       0
 1070.36    .016       0 1129.72     .12       0 1339.41     .08       0
 1369.36    .016       0 1429.27     .12       0 1512.35     .06       0
 1519.14     .08       0
#XS Ineff= 2 , 0
          595.47 1607.01
Permanent Ineff=
       F       F
#Block Obstruct= 1 ,-1
 1279.72 1314.38    1670
Bank Sta=809.1,1023.9
XS Rating Curve= 0 ,0
Exp/Cntr=0.3,0.1

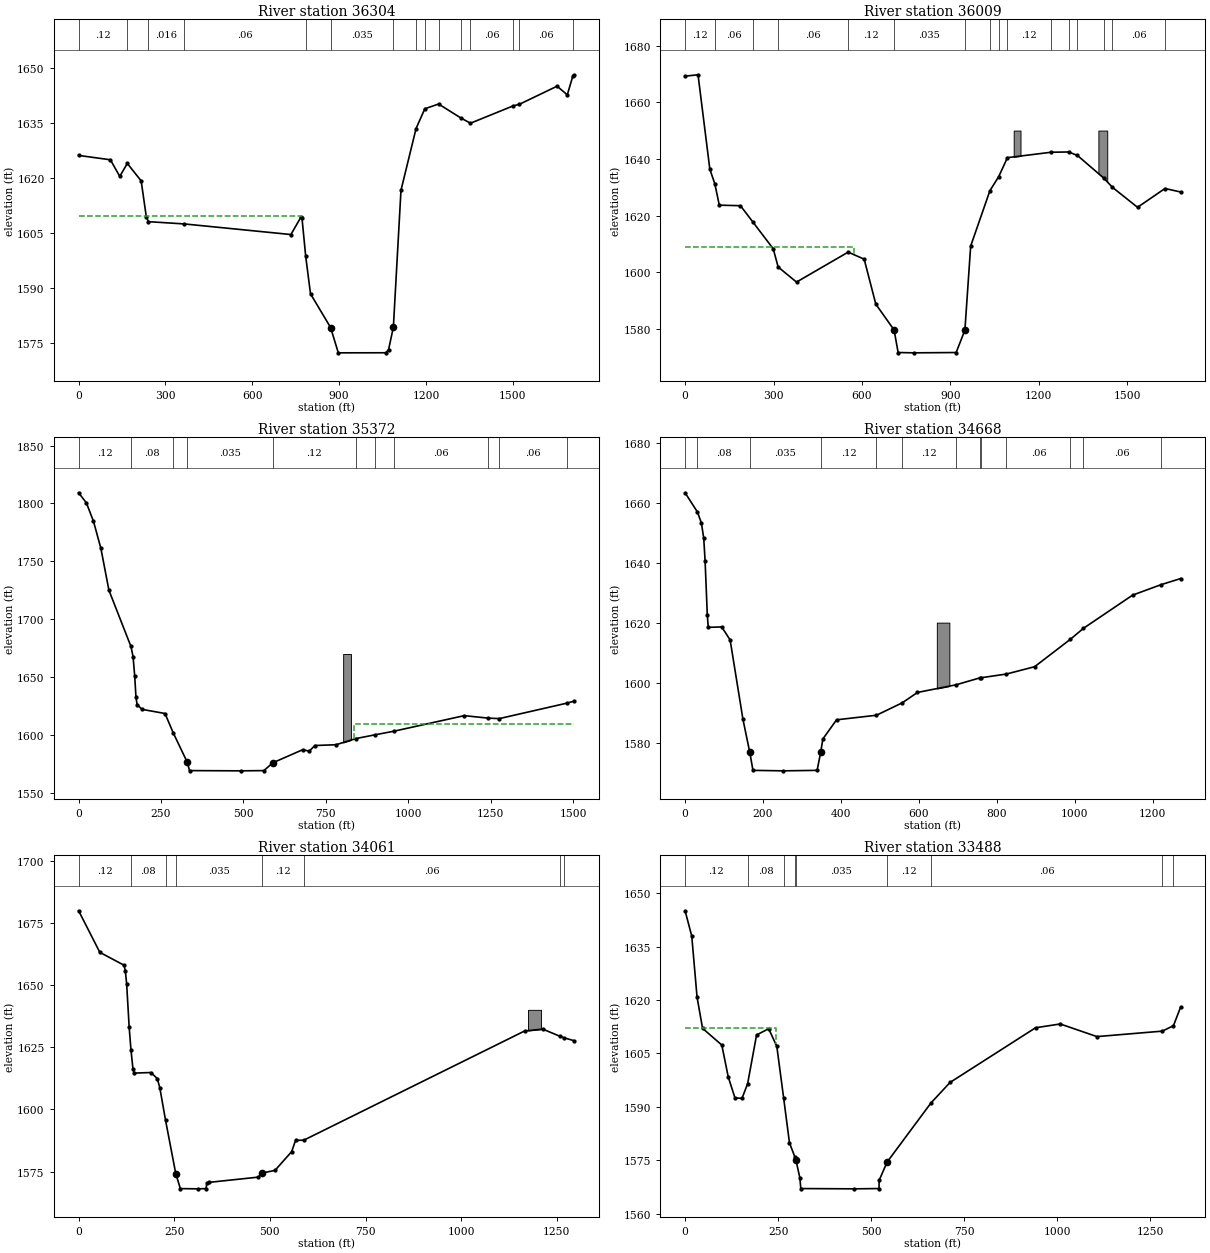
Type RM Length L Ch R = 1 ,36304   ,304.1,295.2,289.6
XS GIS Cut Line= 4
2096355.56375937271478.725802208 2095648.8404878271766.531659409
2095181.95543056271731.3553879732094715.07037333271846.477730853
#Sta/Elev= 30
       0 1626.13   109.8 1624.94   142.1  1620.4   168.2 1623.94   216.1 1619.17
   233.8 1609.37   240.9 1608.03   364.9 1607.41   733.4 1604.51   768.3 1609.29
   771.6 1609.15   784.5  1598.6   801.2  1588.3   870.6  1579.1  897.23 1572.18
  1061.2  1572.2    1071 1573.09  1087.5 1579.19  1113.8 1616.61  1165.9 1633.48
  1196.1 1638.88  1243.8 1640.18  1320.1 1636.39  1353.9 1634.93  1501.3 1639.67
  1522.6 1640.09  1653.1 1645.05  1688.4 1642.69  1707.4 1647.77  1712.2 1648.17
#Mann= 15 ,-1 , 0
       0     .12       0   168.2     .06       0   240.9    .016       0
   364.9     .06       0   784.5     .12       0   870.6    .035       0
  1087.5     .12       0  1165.9     .08       0  1196.1     .12       0
  1243.8     .06       0  1320.1    .016       0  1353.9     .06       0
  1501.3     .12       0  1522.6     .06       0  1707.4     .12       0
#XS Ineff= 2 , 0
          769.48 1609.48
Permanent Ineff=
       F       F
Bank Sta=870.6,1087.5
XS Rating Curve= 0 ,0
Exp/Cntr(USF)=0,0
Exp/Cntr=0.3,0.1

Type RM Length L Ch R = 1 ,36009   ,696,637,579.1
XS GIS Cut Line= 4
2096231.95723391271196.305904901     2095637.844      271459.549
     2095272.991      271452.3162094610.01869318271383.625874225
#Sta/Elev= 30
       0 1669.19    43.9 1669.68    83.9 1636.38   100.91631.215     116 1623.69
   187.8  1623.5  230.131617.729     299  1608.3  315.751601.866     378 1596.56
  553.211607.121   607.6 1604.64   647.1 1588.77  709.08 1579.66   722.8 1571.71
  776.82  1571.6   919.6 1571.71   949.3 1579.59   968.9 1609.25 1034.27 1628.82
 1063.971633.742 1093.661640.446 1242.141642.359 1301.531642.453 1331.221641.211
 1420.311633.249 1450.011629.974  1535.1 1622.93 1628.181629.567  1681.3 1628.33
#Mann= 16 ,-1 , 0
       0     .12       0   100.9     .06       0  230.13    .016       0
  315.75     .06       0  553.21     .12       0  709.08    .035       0
   949.3     .12       0 1034.27    .016       0 1063.97     .08       0
 1093.66     .12       0 1242.14     .06       0 1301.53    .016       0
 1331.22     .06       0 1420.31     .12       0 1450.01     .06       0
 1628.18     .12       0
#XS Ineff= 2 , 0
          571.43    1609
Permanent Ineff=
       F       F
#Block Obstruct= 2 ,-1
 1114.85 1137.99    1650 1402.21 1432.25    1650
Bank Sta=709.08,949.3
XS Rating Curve= 0 ,0
Exp/Cntr=0.3,0.1

Type RM Length L Ch R = 1 ,35372   ,791.3,703.9,548.8
XS GIS Cut Line= 4
2095864.78550384270632.860391612       2095605.1      270762.988
     2095223.872      270894.9052094526.14576988271305.901579808
#Sta/Elev= 30
       0 1809.21    23.6 1800.45    45.1 1784.55    67.6  1761.1    91.9 1725.02
  158.621676.549   165.2 1667.77   170.1 1651.13     174 1632.57   177.4 1626.33
   192.1 1622.17   262.1 1618.58  287.161601.791   329.6 1576.48   336.5 1569.27
  492.86 1569.06   562.2 1569.27     589 1575.99   680.2 1587.35   699.5 1586.04
     717 1590.93     781  1591.6  841.291596.936  899.341600.174  957.681603.353
  1170.1 1616.73 1242.161614.589 1276.441614.174 1482.141627.563  1503.6  1629.3
#Mann= 11 ,-1 , 0
       0     .12       0  158.62     .08       0  287.16     .12       0
   329.6    .035       0     589     .12       0  841.29    .016       0
  899.34     .12       0  957.68     .06       0 1242.16    .016       0
 1276.44     .06       0 1482.14     .12       0
#XS Ineff= 2 , 0
                          835.38         1609.79
Permanent Ineff=
       F       F
#Block Obstruct= 1 ,-1
  802.62  826.23    1670
Bank Sta=329.6,589
XS Rating Curve= 0 ,0
Exp/Cntr=0.3,0.1

Type RM Length L Ch R = 1 ,34668   ,627.7,606.3,546.9
XS GIS Cut Line= 4
     2095027.216      270142.835     2094987.361      270240.286
     2094848.264      270521.1372094458.71068286271280.359153295
#Sta/Elev= 30
       0 1663.26   31.741656.848    41.9 1653.16    47.9 1648.05    51.4 1640.37
      57 1622.61    59.5 1618.42      94 1618.57   115.6 1614.22   148.5 1587.78
     166 1576.81   174.2 1570.78   251.9 1570.62   338.9 1570.78  348.08 1576.83
   353.6 1581.23   388.8 1587.62  491.291589.145  557.691593.303   596.5 1596.74
  695.441599.282  756.881601.601  760.151601.641  824.861602.872   897.2 1605.31
  989.261614.477 1022.461618.098  1148.7 1629.16 1221.651632.643    1272 1634.68
#Mann= 13 ,-1 , 0
       0     .12       0   31.74     .08       0     166    .035       0
  348.08     .12       0  491.29     .06       0  557.69     .12       0
  695.44    .016       0  756.88     .12       0  760.15    .016       0
  824.86     .06       0  989.26    .016       0 1022.46     .06       0
 1221.65     .12       0
#Block Obstruct= 1 ,-1
  646.16  678.32    1620
Bank Sta=166,348.08
XS Rating Curve= 0 ,0
Exp/Cntr=0.3,0.1

Type RM Length L Ch R = 1 ,34061   ,560,573.1,576.1
XS GIS Cut Line= 4
     2094411.214      269860.324      2094381.22      270024.769
      2094303.44      270414.6092094124.53582309 271123.08280579
#Sta/Elev= 30
       0 1679.81    55.4 1663.11   118.8 1657.92   122.1 1655.58   125.5 1650.55
   132.1 1633.05  136.86  1623.8   142.2 1616.06   145.5 1614.58   188.9 1614.81
   205.6 1612.39   212.3 1608.62  227.121595.697  253.93 1574.17   265.9 1568.16
  311.71 1568.07   332.8 1568.16   335.5 1570.35   339.5 1570.65   469.9 1572.78
     480 1574.42   513.4  1575.5   556.9 1583.02     567 1587.54  588.821587.641
  1165.9 1631.51  1213.3 1632.26 1259.041629.321 1268.321628.795  1295.4 1627.59
#Mann= 8 ,-1 , 0
       0     .12       0  136.86     .08       0  227.12     .12       0
  253.93    .035       0     480     .12       0  588.82     .06       0
 1259.04     .12       0 1268.32     .06       0
#Block Obstruct= 1 ,-1
 1174.71 1208.83    1640
Bank Sta=253.93,480
XS Rating Curve= 0 ,0
Exp/Cntr=0.3,0.1

Type RM Length L Ch R = 1 ,33488   ,602.3,591.1,570.9
XS GIS Cut Line= 4
     2093941.097       269695.29     2093834.988      269920.452
     2093738.038      270297.5322093692.80875052270988.894381462
#Sta/Elev= 30
       0 1645.03    17.9 1637.91    32.1 1620.82    46.9 1612.06    98.6 1607.37
     116 1598.38   133.9 1592.57   152.8  1592.4  167.99 1596.54     192 1610.21
   224.6 1611.94   246.4 1606.99  264.821592.425   280.4 1579.92  295.321575.862
   297.5 1575.22   308.3  1570.1   310.8 1567.12  453.81 1567.04   520.9 1567.12
   521.2 1569.41   542.71574.564  660.611591.146   711.8 1596.89   941.4 1612.22
  1007.7 1613.28  1106.3 1609.74 1282.221611.277 1311.821612.809  1331.1 1618.03
#Mann= 9 ,-1 , 0
       0     .12       0  167.99     .08       0  264.82     .12       0
  295.32     .08       0   297.5    .035       0   542.7     .12       0
  660.61     .06       0 1282.22     .12       0 1311.82    .016       0
#XS Ineff= 2 , 0
          242.86 1612.25
Permanent Ineff=
       F       F
Bank Sta=297.5,542.7
XS Rating Curve= 0 ,0
Exp/Cntr=0.3,0.1

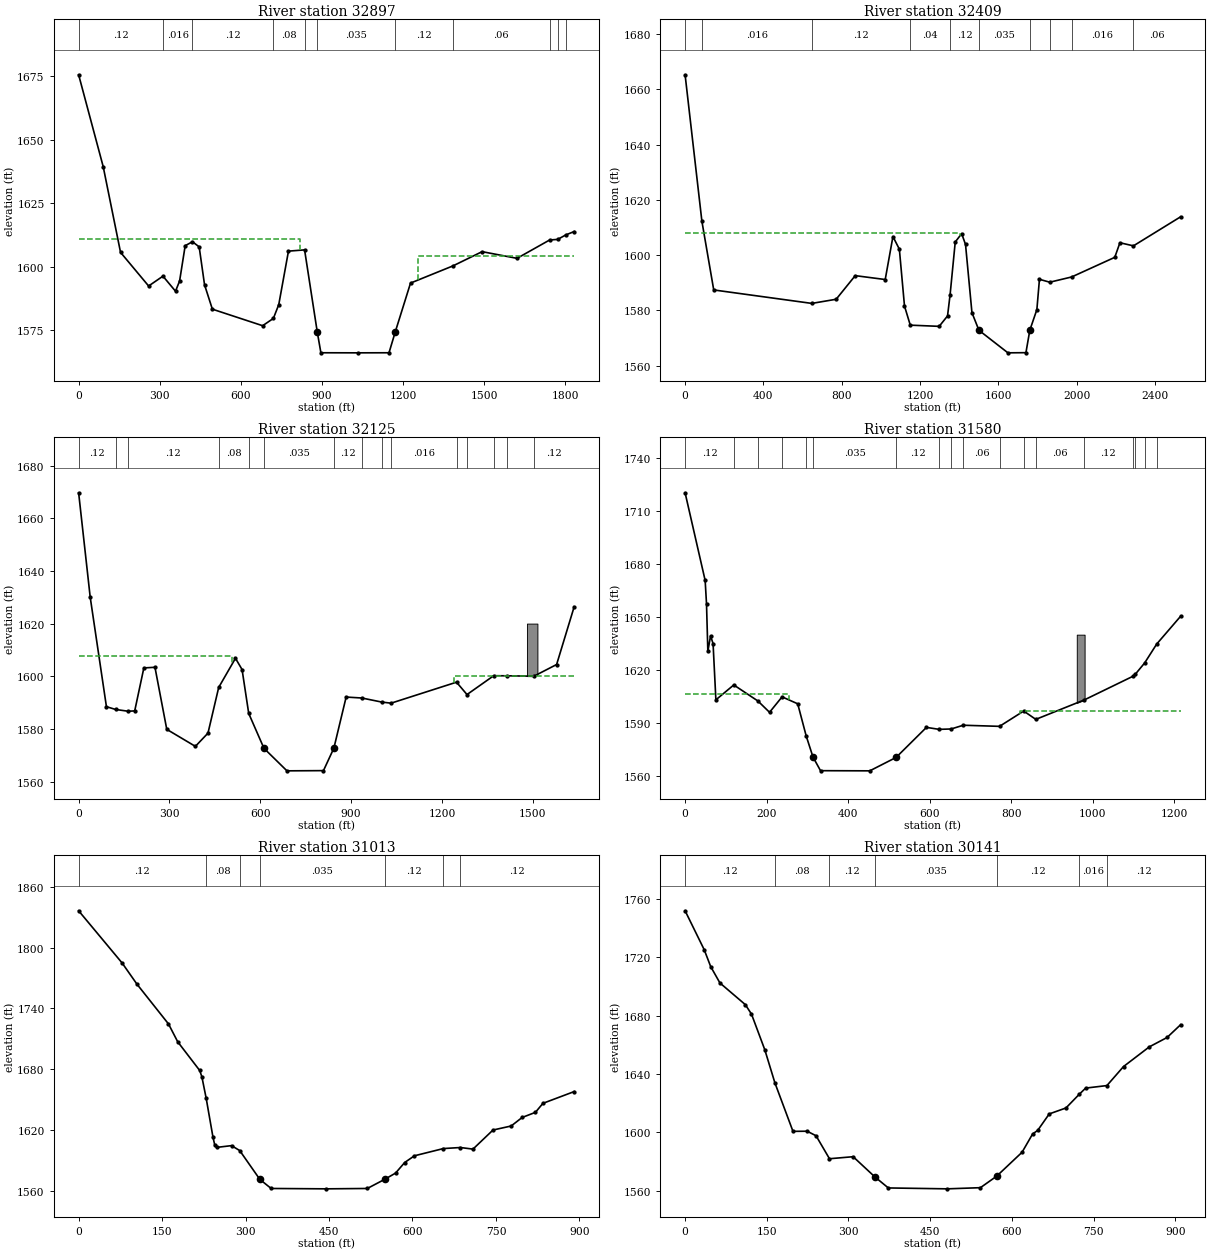
Type RM Length L Ch R = 1 ,32897   ,519.8,488.3,470.2
XS GIS Cut Line= 4
2093710.18180715269146.950036027     2093234.691      269839.009
     2093179.042      270209.9792093095.36611311270823.351903134
#Sta/Elev= 30
       0 1675.67    90.9 1639.45   155.1 1605.64     259 1592.37  312.081596.249
   358.5 1590.31   373.6 1594.32   394.3 1608.26   421.2 1609.83   446.1  1607.8
     466 1592.82   494.9 1583.23   680.9 1576.71   720.7 1579.59   740.6 1585.03
   776.5 1606.12   836.2 1606.61   883.2 1574.16   896.5 1566.04 1032.19 1566.01
  1148.6 1566.04  1171.1 1574.05  1228.2 1593.52 1385.261600.299  1493.1 1605.91
  1622.3 1603.28 1742.991610.516  1772.81610.746 1802.611612.508  1833.8 1613.85
#Mann= 11 ,-1 , 0
       0     .12       0  312.08    .016       0   421.2     .12       0
   720.7     .08       0   836.2     .12       0   883.2    .035       0
  1171.1     .12       0 1385.26     .06       0 1742.99    .016       0
  1772.8     .08       0 1802.61     .06       0
#XS Ineff= 2 , 0
          820.86 1611.07 1255.66         1604.33
Permanent Ineff=
       F       F
Bank Sta=883.2,1171.1
XS Rating Curve= 0 ,0
Exp/Cntr=0.3,0.1

Type RM Length L Ch R = 1 ,32409   ,217.5,284,310.4
BEGIN DESCRIPTION:
Not Burnt
END DESCRIPTION:
XS GIS Cut Line= 6
2093686.59770919269131.5261133252092717.06900705269348.143390051
2092714.03753494269429.993136884     2092710.967      269762.108
      2092719.29        270079.82092665.76206745270883.755838917
#Sta/Elev= 30
       01665.307  85.7391612.283  146.251587.374 647.147  1582.5 771.531    1584
 869.0211592.5561022.1191591.1461061.5161606.6981094.3341602.1541120.5821581.543
1150.111 1574.621297.7551574.1881340.4071577.9581353.5311585.6741379.779 1604.75
 1412.591607.7711432.2821603.8531465.1021579.1441500.7991572.7651648.8911564.594
1740.8151564.6561760.7051572.7921796.7131580.2541809.8651591.2271862.4751590.177
 1974.271592.0742194.5731599.1882220.8771604.4692289.9271603.3442531.0051613.875
#Mann= 10 ,-1 , 0
       0     .12       0  85.739    .016       0 647.147     .12       0
1150.111     .04       01353.531     .12       01500.799    .035       0
1760.705     .12       01862.475     .06       0 1974.27    .016       0
2289.927     .06       0
#XS Ineff= 2 , 0
         1402.46    1608
Permanent Ineff=
       F       F
Bank Sta=1500.799,1760.705
XS Rating Curve= 0 ,0
Exp/Cntr=0.3,0.1

Type RM Length L Ch R = 1 ,32125   ,578.1,544.5,510.8
BEGIN DESCRIPTION:
Not Burnt
END DESCRIPTION:
XS GIS Cut Line= 5
2092248.18242261269298.198072966     2092512.287      269758.741
      2092403.13      270099.1042092286.13927023270373.858123925
2091952.23153874 270674.95281432
#Sta/Elev= 30
       0 1669.66    38.2 1630.05    91.8 1588.46   122.11587.399  163.371586.726
   185.2 1586.85   215.4 1603.17   252.1 1603.41   291.1 1579.85   385.6 1573.39
   427.2 1578.42   462.61595.772     518 1606.83   539.8 1602.55  561.741585.889
   612.1 1572.65  687.99  1564.1   808.6 1564.18     843 1572.73   883.5 1592.11
  935.561591.746 1001.091590.204 1031.871589.787 1248.021597.756 1282.631593.058
 1370.841600.208 1414.941600.182  1503.5 1600.02  1578.6 1604.46  1636.6 1626.39
#Mann= 15 ,-1 , 0
       0     .12       0   122.1    .016       0  163.37     .12       0
   462.6     .08       0  561.74     .12       0   612.1    .035       0
     843     .12       0  935.56    .016       0 1001.09     .08       0
 1031.87    .016       0 1248.02     .12       0 1282.63     .06       0
 1370.84     .12       0 1414.94     .06       0  1503.5     .12       0
#XS Ineff= 2 , 0
          508.16 1607.54 1241.04         1600.21
Permanent Ineff=
       F       F
#Block Obstruct= 1 ,-1
 1480.61 1515.21    1620
Bank Sta=612.1,843
XS Rating Curve= 0 ,0
Exp/Cntr=0.3,0.1

Type RM Length L Ch R = 1 ,31580   ,541.3,567.1,588.4
BEGIN DESCRIPTION:
Not Burnt
END DESCRIPTION:
XS GIS Cut Line= 4
     2091944.696      269432.688     2091926.352      269694.759
     2091906.404      269983.3792091846.86111311270643.946215893
#Sta/Elev= 30
       0 1720.15    49.2 1670.61    52.5 1657.47    55.8 1630.56    62.4 1639.29
    68.6 1634.99    75.5 1603.18  119.391611.588  178.61 1602.52   207.1 1596.13
  237.831604.866   276.2 1600.94  297.051582.724  313.61 1570.89   332.1 1563.16
  452.94 1563.07   517.5 1570.65   591.9 1587.62  622.851586.509  652.511586.716
  682.161588.831  771.141588.202  830.45 1596.85  860.111592.146  978.741603.104
 1097.361616.377 1104.511617.757 1127.021624.008 1156.681634.723  1215.3 1650.41
#Mann= 18 ,-1 , 0
       0     .12       0  119.39    .016       0  178.61     .12       0
  237.83     .08       0  297.05     .12       0  313.61    .035       0
   517.5     .12       0  622.85    .016       0  652.51     .08       0
  682.16     .06       0  771.14    .016       0  830.45     .08       0
  860.11     .06       0  978.74     .12       0 1097.36    .016       0
 1104.51     .12       0 1127.02    .016       0 1156.68     .12       0
#XS Ineff= 2 , 0
          253.97 1606.71  820.85         1597.11
Permanent Ineff=
       F       F
#Block Obstruct= 1 ,-1
  960.58  979.77    1640
Bank Sta=313.61,517.5
XS Rating Curve= 0 ,0
Exp/Cntr=0.3,0.1

Type RM Length L Ch R = 1 ,31013   ,816.4,872.1,903.7
XS GIS Cut Line= 4
  2091445.681616269355.6332639912091398.09153726269622.509528835
2091300.67764926270000.357336857  2091240.552216 270221.67409601
#Sta/Elev= 30
       0 1836.23    78.2 1784.75   104.8 1763.95   161.5 1724.73   178.1 1707.12
   217.6 1678.88   221.5 1672.66  229.231651.493   241.5 1613.01   244.8  1605.1
   248.1 1603.09   274.8 1604.84  289.531599.949   325.7 1571.57     346 1562.62
  445.29 1562.26   518.8 1562.62   550.2 1571.66   569.6 1577.78     586  1588.2
   603.5 1594.82  655.571601.949  686.161602.974   708.7 1601.39   744.7  1620.2
   777.4 1624.19   797.1 1632.59   820.9 1637.61   834.5 1646.51   890.6 1658.09
#Mann= 7 ,-1 , 0
       0     .12       0  229.23     .08       0  289.53     .12       0
   325.7    .035       0   550.2     .12       0  655.57    .016       0
  686.16     .12       0
Bank Sta=325.7,550.2
XS Rating Curve= 0 ,0
Exp/Cntr=0.3,0.1

Type RM Length L Ch R = 1 ,30141   ,523.4,580.9,614.9
BEGIN DESCRIPTION:
Not Burnt
END DESCRIPTION:
XS GIS Cut Line= 3
     2090858.625      269033.356     2090594.819      269404.073
     2090331.012       269774.79
#Sta/Elev= 30
       0 1751.98      35 1725.34    47.1  1713.6      64 1702.43   110.6 1687.58
   121.9  1681.1   146.4 1656.57  164.941633.872   198.1 1600.62   224.2 1600.71
   240.5 1597.59  265.141581.828   308.6 1583.22   348.2 1569.46   373.2 1561.78
  481.52 1561.17   542.3 1561.96   572.2 1569.87   618.8 1586.28   638.1 1598.78
   647.5  1601.3   668.7 1612.58   699.4 1616.66  723.671626.003   735.6  1630.3
  774.611632.035   805.1 1645.08   852.4 1658.58   885.1 1665.03     910 1673.81
#Mann= 7 ,-1 , 0
       0     .12       0  164.94     .08       0  265.14     .12       0
   348.2    .035       0   572.2     .12       0  723.67    .016       0
  774.61     .12       0
Bank Sta=348.2,572.2
XS Rating Curve= 0 ,0
Exp/Cntr=0.3,0.1

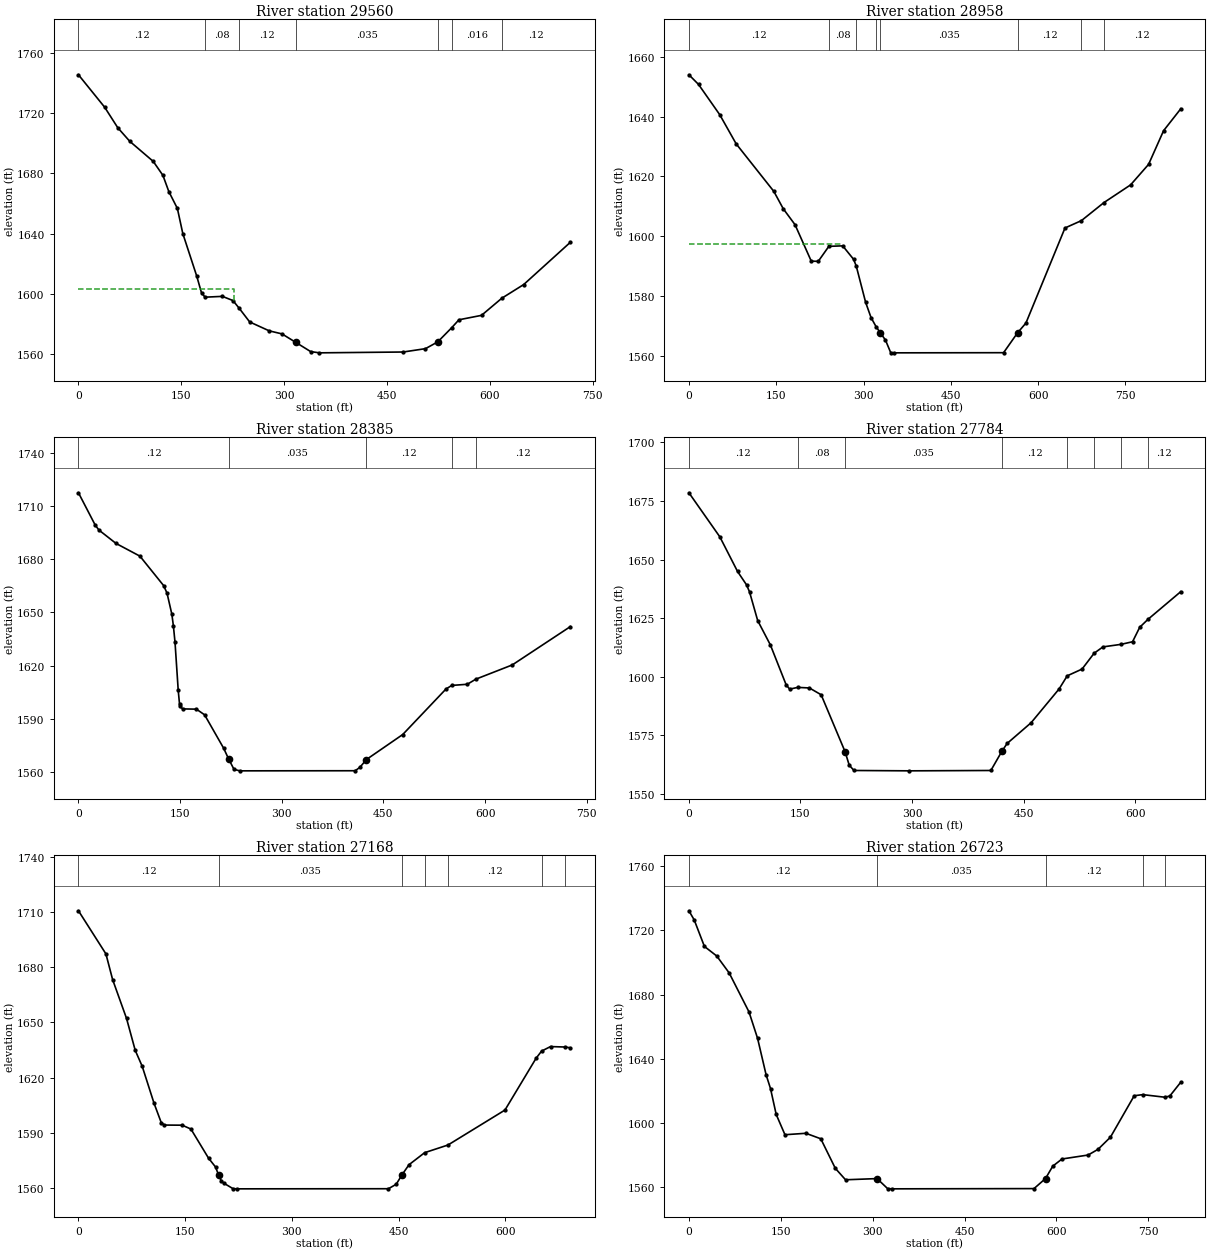
Type RM Length L Ch R = 1 ,29560   ,623.3,602.5,591.2
BEGIN DESCRIPTION:
Not Burnt
END DESCRIPTION:
XS GIS Cut Line= 2
     2090553.074      268733.559     2089974.484      269157.911
#Sta/Elev= 30
       0 1745.53    38.3 1723.94    57.4 1710.32    74.9 1701.31   109.1 1687.99
   123.2 1678.72   131.8 1667.98   144.3 1656.73   152.2 1640.09   172.5 1611.85
   179.5 1600.66  184.741597.796     210 1598.33   225.4 1595.54  234.681590.291
   249.8 1581.33   278.3 1575.42   296.8 1573.42   316.6 1567.89   338.7 1561.65
   351.5 1560.82   473.6 1561.37   506.2  1563.6   524.1  1568.1  544.311577.464
     555 1582.78   587.9 1585.72  617.57 1597.11   649.4 1606.17   717.5 1634.26
#Mann= 7 ,-1 , 0
       0     .12       0  184.74     .08       0  234.68     .12       0
   316.6    .035       0   524.1     .12       0  544.31    .016       0
  617.57     .12       0
#XS Ineff= 2 , 0
          226.76 1603.29
Permanent Ineff=
       F       F
Bank Sta=316.6,524.1
XS Rating Curve= 0 ,0
Exp/Cntr=0.3,0.1

Type RM Length L Ch R = 1 ,28958   ,591.1,573.4,541.6
XS GIS Cut Line= 4
     2090166.047      268142.927     2090025.573      268337.999
     2089718.949      268625.839     2089599.692      268766.153
#Sta/Elev= 30
       0 1653.99    16.5 1650.77    52.9 1640.65    81.2 1630.87   145.9 1614.96
   162.1 1609.14   182.3 1603.82   210.2 1591.62   222.2 1591.55  240.381596.567
   264.2 1596.74   282.8 1592.26  287.431590.019   303.6 1577.83   312.9 1572.73
  321.411569.734   328.7 1567.65   337.7  1565.2   346.7 1560.98  352.62 1560.93
   540.6 1560.98   564.6 1567.63     579  1570.9   646.1 1602.72  674.311605.177
  713.071611.226   758.8 1617.14   789.7    1624   815.5 1635.28   845.1 1642.63
#Mann= 8 ,-1 , 0
       0     .12       0  240.38     .08       0  287.43     .06       0
  321.41     .12       0   328.7    .035       0   564.6     .12       0
  674.31    .016       0  713.07     .12       0
#XS Ineff= 2 , 0
           261.9 1597.37
Permanent Ineff=
       F       F
Bank Sta=328.7,564.6
XS Rating Curve= 0 ,0
Exp/Cntr=0.3,0.1

Type RM Length L Ch R = 1 ,28385   ,600.8,600.7,600.1
XS GIS Cut Line= 3
     2089647.389      267830.852     2089383.584       268201.57
     2089234.271      268427.488
#Sta/Elev= 30
       0 1717.65    24.8 1699.33    30.3 1696.55    55.4 1689.02    90.7 1681.83
   125.7 1665.17   130.7  1660.9   137.8 1649.02   140.1 1642.38   142.5 1633.08
   147.2 1606.02   149.1 1598.36   149.8 1596.85   153.9 1595.48     174 1595.33
   186.1 1592.14   214.3  1573.2   221.4 1567.32   229.5  1561.3  238.04 1560.46
   408.3 1560.52   415.4 1562.48   424.8 1566.83   478.5    1581   542.4 1606.77
  550.871608.747   573.8  1609.4  586.281612.276   640.1 1620.33   725.8    1642
#Mann= 5 ,-1 , 0
       0     .12       0   221.4    .035       0   424.8     .12       0
  550.87    .016       0  586.28     .12       0
Bank Sta=221.4,424.8
XS Rating Curve= 0 ,0
Exp/Cntr=0.3,0.1

Type RM Length L Ch R = 1 ,27784   ,637.3,615.8,595.9
XS GIS Cut Line= 3
     2089158.531      267482.977     2088894.725      267853.694
      2088775.72      268022.365
#Sta/Elev= 30
       0 1678.46    41.6 1659.66    65.4  1644.9    77.5 1639.19    81.5 1636.21
    92.5 1623.94   109.5 1613.61   130.8 1596.53   135.5 1594.74   146.31595.481
     162 1595.24   177.8 1592.34     210 1568.04   215.5 1562.35   221.9 1560.05
  296.58  1559.9     406 1560.05   420.7 1568.18   427.8 1571.56   460.1 1580.41
   497.8 1594.84  508.671600.411   528.6 1603.29  544.821610.042   556.7 1612.75
  580.961613.827   596.5 1614.94   606.1 1621.09  617.111624.465   661.4 1636.32
#Mann= 8 ,-1 , 0
       0     .12       0   146.3     .08       0     210    .035       0
   420.7     .12       0  508.67    .016       0  544.82     .12       0
  580.96    .016       0  617.11     .12       0
Bank Sta=210,420.7
XS Rating Curve= 0 ,0
Exp/Cntr=0.3,0.1

Type RM Length L Ch R = 1 ,27168   ,404,445.5,472.9
XS GIS Cut Line= 4
     2088572.375      267162.439     2088505.026      267297.137
     2088358.723      267613.577     2088274.065      267786.136
#Sta/Elev= 30
       0 1710.61    38.6 1687.19      48 1673.25    67.6 1652.09    79.8 1634.76
    89.6 1626.11   106.2 1606.06   116.5 1595.35   120.8 1594.16   145.8 1594.09
   158.1 1591.99   182.8  1576.2   192.7 1571.36   197.2 1566.79   200.8 1563.77
   204.4 1562.56   217.4 1559.56  223.49  1559.5   435.7 1559.56   446.6 1561.98
   454.7 1567.06   464.6 1572.61  486.631579.158  519.391583.317   599.5 1602.32
   643.3  1630.5  650.991634.362   663.5 1636.81  683.891636.573   691.4 1636.14
#Mann= 7 ,-1 , 0
       0     .12       0   197.2    .035       0   454.7     .12       0
  486.63    .016       0  519.39     .12       0  650.99    .016       0
  683.89     .12       0
Bank Sta=197.2,454.7
XS Rating Curve= 0 ,0
Exp/Cntr=0.3,0.1

Type RM Length L Ch R = 1 ,26723   ,413.5,411.9,413.5
XS GIS Cut Line= 2
2088279.52211555266941.5695188382087810.48263651267593.454896485
#Sta/Elev= 30
       0 1732.15     8.7 1726.41    25.3 1709.96    45.5 1703.97    65.7 1693.47
    98.1 1669.18   112.1 1652.73     126 1630.07   133.2 1621.48   142.5 1605.36
   156.8 1592.74     191 1593.63   215.3 1590.21     239 1571.83   255.7 1564.69
   307.2 1565.43   324.4  1559.2  331.08 1559.05   563.4  1559.2   582.2 1565.47
     594 1573.16   609.1 1577.63   651.8  1580.1     668 1583.67   688.2 1591.21
     727    1617  740.991617.695  777.381616.069   785.2 1616.87   803.1 1625.47
#Mann= 5 ,-1 , 0
       0     .12       0   307.2    .035       0   582.2     .12       0
  740.99    .016       0  777.38     .12       0
Bank Sta=307.2,582.2
XS Rating Curve= 0 ,0
Exp/Cntr=0.3,0.1