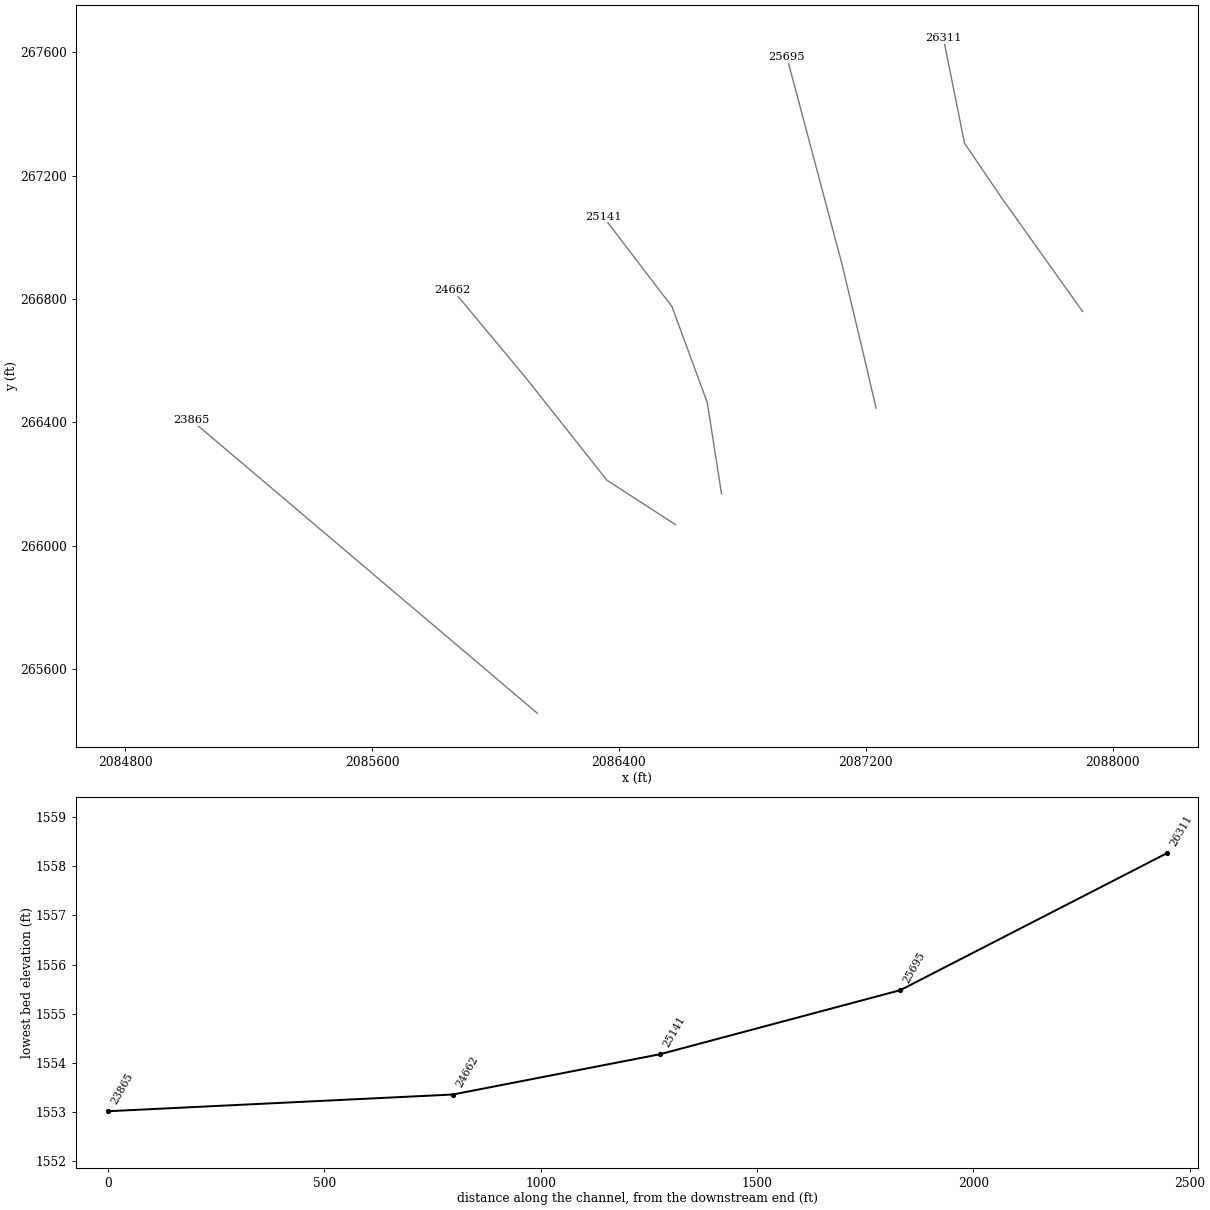
HEC-RAS study GRBRRV3.prj: GRBRRV3

--- GRBRRV3.g01 (geometry) --- (continued)

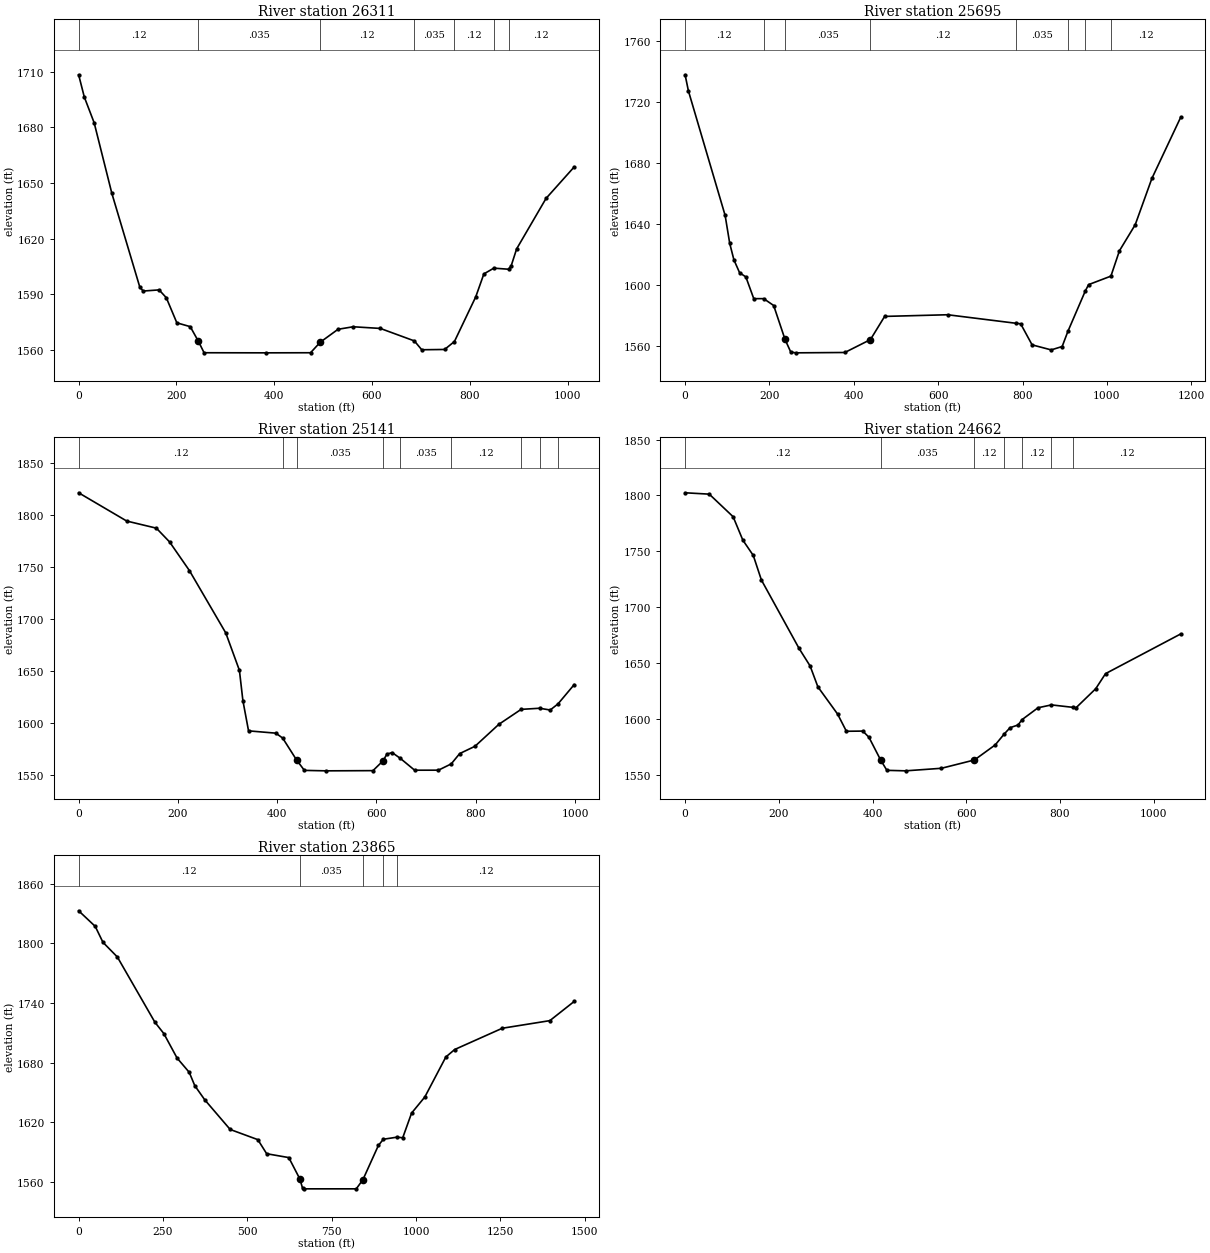
Type RM Length L Ch R = 1 ,26311   ,654.2,615.2,506.7
XS GIS Cut Line= 4
     2087901.955      266759.077      2087638.15      267129.795
2087519.24763304267305.239768704  2087451.095336267645.157864008
#Sta/Elev= 30
       0 1708.41    11.6  1696.4    31.8 1682.46      68 1644.32   125.2 1593.69
   132.1 1591.63   164.6 1592.25   179.3 1588.03   200.9 1574.46   228.3  1572.4
     245 1564.47   256.6 1558.31  382.67 1558.26   474.4 1558.31   494.2 1563.99
   530.6 1570.98   561.6 1572.34   617.1 1571.44   686.7  1564.7   701.8 1559.92
   748.6 1560.08   768.7 1564.38   812.3 1588.51   828.9 1600.88  849.211603.991
  879.341603.408   884.7  1605.2   895.9 1614.39   956.1 1641.66  1013.6 1658.63
#Mann= 7 ,-1 , 0
       0     .12       0     245    .035       0   494.2     .12       0
   686.7    .035       0   768.7     .12       0  849.21    .016       0
  879.34     .12       0
Bank Sta=245,494.2
XS Rating Curve= 0 ,0
Exp/Cntr=0.3,0.1

Type RM Length L Ch R = 1 ,25695   ,545.2,554.4,587.6
XS GIS Cut Line= 4
     2087232.726      266445.884     2087192.841      266617.541
     2087122.027      266914.279  2086943.897344267584.619456012
#Sta/Elev= 30
       0 1738.13     7.9 1727.49    94.9 1645.77   105.8 1627.39   115.7 1616.58
   129.2 1608.12   144.1 1605.32   162.8 1591.07  186.321591.075     210 1586.57
     237 1564.25   250.5    1556     262 1555.48   378.7 1555.71   439.4 1564.17
   473.1 1579.41   622.5  1580.5   785.4 1574.87   795.6 1574.56   822.7 1560.72
     868 1557.41     894 1559.63   907.6 1569.59  948.481595.869   956.6 1600.28
  1009.61605.872  1029.8 1622.53  1067.2 1639.62  1106.7 1670.02  1174.9 1710.13
#Mann= 8 ,-1 , 0
       0     .12       0  186.32     .08       0     237    .035       0
   439.4     .12       0   785.4    .035       0   907.6     .12       0
  948.48    .016       0  1009.6     .12       0
Bank Sta=237,439.4
XS Rating Curve= 0 ,0
Exp/Cntr=0.3,0.1

Type RM Length L Ch R = 1 ,25141   ,455.7,479.2,517.7
XS GIS Cut Line= 4
  2086732.235616 266167.56877599     2086686.134      266463.714
     2086571.935       266774.72     2086349.229      267066.779
#Sta/Elev= 30
       0 1821.27    96.9 1794.11   156.6 1787.28   183.2 1774.07   223.1  1746.6
   296.4 1686.67   323.9 1650.73   330.9 1621.68   342.3 1592.58   397.3 1590.37
  411.081585.629   439.2 1564.52   454.8 1554.62  497.92 1554.18     593 1554.38
   613.3 1563.81     621 1570.23   631.5 1571.74     648 1566.19   676.9 1554.79
   724.8 1554.81   750.6 1560.84   767.7 1570.76   798.5 1577.77   846.5 1598.83
   891.4 1613.22  928.551614.299     950 1612.61  965.691618.455   998.3 1636.99
#Mann= 9 ,-1 , 0
       0     .12       0  411.08     .08       0   439.2    .035       0
   613.3     .12       0     648    .035       0   750.6     .12       0
   891.4    .016       0  928.55     .08       0  965.69     .12       0
Bank Sta=439.2,613.3
XS Rating Curve= 0 ,0
Exp/Cntr=0.3,0.1

Type RM Length L Ch R = 1 ,24662   ,773.2,797.3,817.7
BEGIN DESCRIPTION:
Not Burnt
END DESCRIPTION:
XS GIS Cut Line= 4
2086582.58205601266068.290639998     2086360.839      266212.166
     2086097.168      266545.543  2085861.894664266828.697208005
#Sta/Elev= 30
       0 1802.33    51.6  1801.1   102.5 1780.88   123.2 1759.95   145.5 1746.22
   162.8 1724.26   243.2 1662.98   266.8 1647.24   283.4 1628.54   325.5 1604.15
   344.2 1588.79   379.2 1588.96   392.3 1583.45  417.041563.238   430.6 1553.81
  470.59 1553.36     547 1555.65   617.5  1563.1   661.8 1576.57  680.641586.155
   693.5 1592.01   710.6 1594.42  718.871599.144   753.2 1609.84  781.821612.401
  828.04 1610.19   834.4 1609.89   876.3 1626.89   897.2 1640.38  1057.5  1675.9
#Mann= 7 ,-1 , 0
       0     .12       0  417.04    .035       0   617.5     .12       0
  680.64    .016       0  718.87     .12       0  781.82    .016       0
  828.04     .12       0
Bank Sta=417.04,617.5
XS Rating Curve= 0 ,0
Exp/Cntr=0.3,0.1

Type RM Length L Ch R = 1 ,23865   ,1022.6,1022.6,1022.6
BEGIN DESCRIPTION:
Burnt; channel copied from Greenbrier 1 Disaster Streams
END DESCRIPTION:
XS GIS Cut Line= 2
     2086136.156      265455.813      2085015.93      266406.117
#Sta/Elev= 30
       0 1832.92    49.2 1817.22    72.1 1801.18   114.8  1786.4   226.2 1720.67
   252.5 1709.36   291.8 1684.69   327.9 1670.31   344.3 1656.89   373.8 1642.67
   449.2 1612.79   531.2 1602.54   557.4 1588.37     623 1584.48   655.8 1562.96
   663.7  1553.8   668.9 1553.02     823 1553.02   842.7  1562.2   888.6 1596.68
  903.251602.928  943.35 1605.01   960.8 1604.47     987 1629.26  1026.3 1645.49
  1088.6 1685.75  1114.9 1693.28  1255.9 1714.67  1396.9 1722.33    1469 1741.65
#Mann= 5 ,-1 , 0
       0     .12       0   655.8    .035       0   842.7     .12       0
  903.25    .016       0  943.35     .12       0
Bank Sta=655.8,842.7
XS Rating Curve= 0 ,0
Exp/Cntr=0.3,0.1
LCMann Table=0

Chan Stop Cuts=-1
Use User Specified Reach Order=0
Composite Channel Slope=5